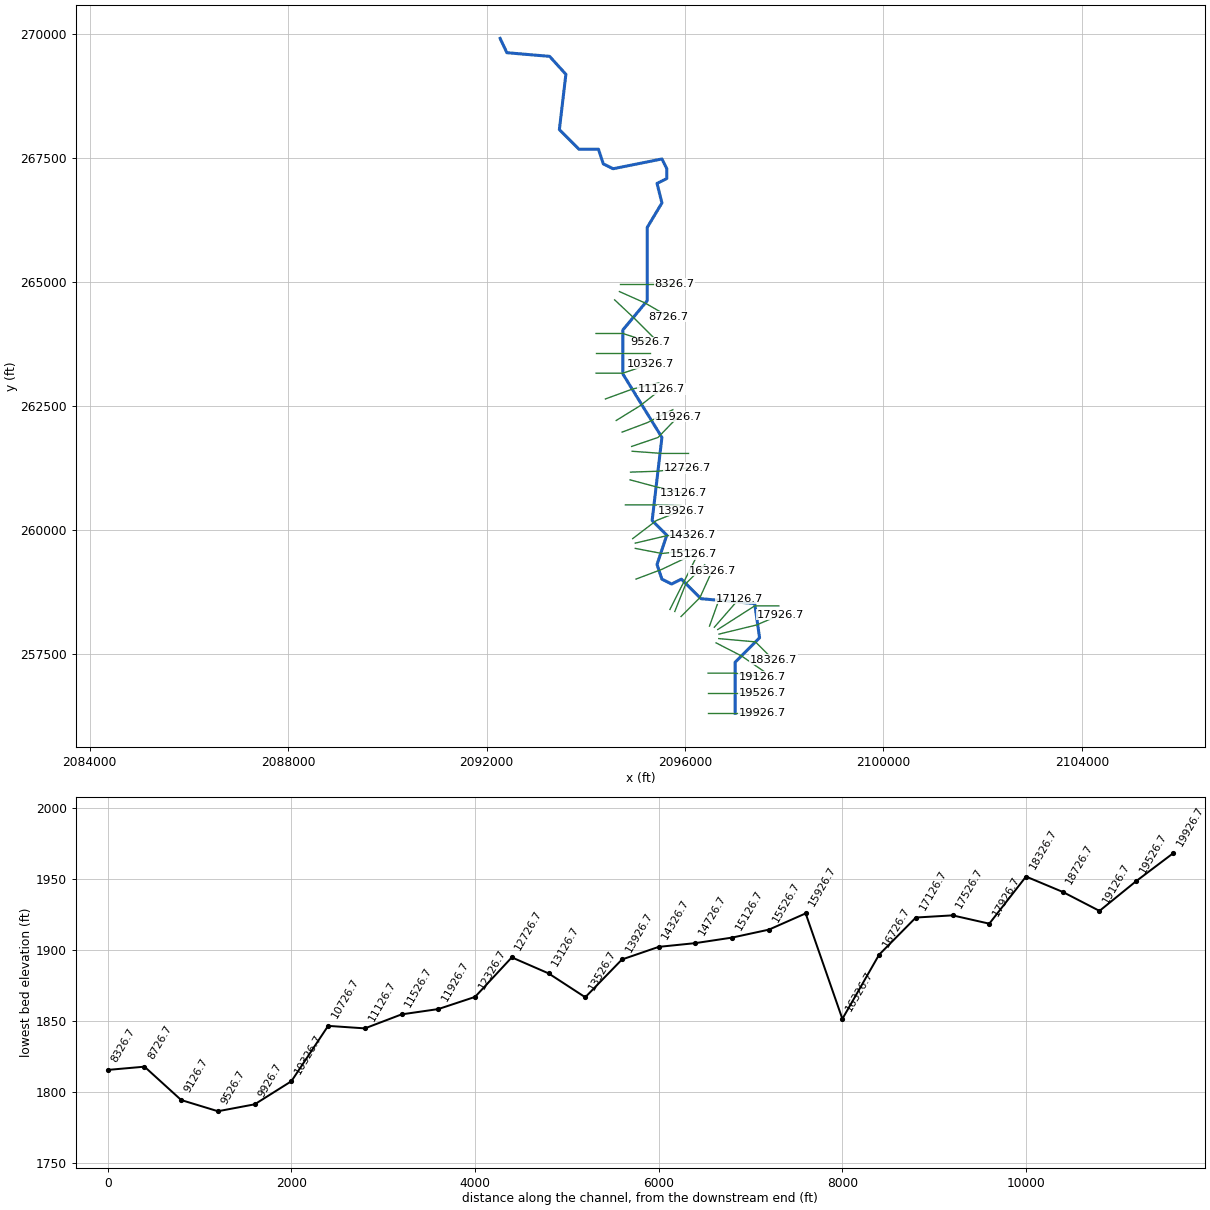
--- GrnbrRvT1.prj (project) ---

Proj Title=GrnbrRvT1
Current Plan=p01
Default Exp/Contr=0,0
English Units
Geom File=g01
Flow File=f01
Plan File=p01
BEGIN DESCRIPTION:
END DESCRIPTION:
DSS Export Rating Curves= 0
DSS Export Rating Curve Sorted= 0
DSS Export Volume Flow Curves= 0
DXF OffsetX= 0
DXF OffsetY= 0
DXF ScaleX= 0
DXF ScaleY= 0

--- GrnbrRvT1.p01 (plan) ---

Plan Title=Floodplain
Program Version=4.00
Geom File=g01
Flow File=f01
K Sum by GR=0
Std Step Tol=0.01
Critical Tol=0.01
Num of Std Step Trials=20
Max Error Tol=0.3
Flow Tol Ratio=0.001
Split Flow NTrial=30
Split Flow Tol=0.02
Split Flow Ratio=0.02
Log Output Level=0
Friction Slope Method=1
Unsteady Friction Slope Method=2
Unsteady Bridges Friction Slope Method=1
Global Log Level=0
CheckData=False
Run HTab=0
Run UNet=0
Run PostProcess=0
UNET Theta=0
UNET Theta Warmup=0
UNET ZTol=0
UNET ZSATol=0
UNET MxIter=0
UNET MaxInSteps=0
UNET DtIC=0
UNET DtMin=0
UNET MaxCRTS=0
UNET WFStab=0
UNET SFStab=0
UNET WFX=0
UNET SFX=0
UNET DSS MLevel=0
UNET DZMax Abort=0
UNET Convert EG Bridges=0
UNET Use Existing IB Tables=0
UNET Froude Limit=0
UNET Froude Power=0
Write IC File=0
Echo Input=False
Echo Output=False
Write Detailed=0

--- GrnbrRvT1.f01 (steady flow) ---

Flow Title=NFF Regression Equation
Program Version=4.00
Number of Profiles=1
Profile Names=P100yr
River Rch & RM=GrnbrRvT1,Main      ,19926.7
1102.052
River Rch & RM=GrnbrRvT1,Main      ,17126.7
1164.951
River Rch & RM=GrnbrRvT1,Main      ,16726.7
1391.015
River Rch & RM=GrnbrRvT1,Main      ,15126.7
1504.552
River Rch & RM=GrnbrRvT1,Main      ,10726.7
1603.527
River Rch & RM=GrnbrRvT1,Main      ,7126.7
1772.808
River Rch & RM=GrnbrRvT1,Main      ,2667.7
1903.867
River Rch & RM=GrnbrRvT1,Main      ,60.6
1924.744
Boundary for River Rch & Prof#=GrnbrRvT1,Main      ,1
Up Type=0
Dn Type=3
Dn Slope=0.009762

--- GrnbrRvT1.g01 (geometry) ---

Geom Title=USGS 10m DEM
Program Version=4.00

River Reach=GrnbrRvT1     ,Main
Reach XY= 30
     2097010.227      256307.287     2097010.227      257338.165
     2097502.347      257830.285     2097403.923      258519.253
     2096321.259      258617.677     2095927.563      259011.373
     2095730.715      258912.949     2095533.867      259011.373
     2095435.443      259306.645     2095632.291      259897.189
     2095337.019      260192.461     2095533.867      261865.669
     2094746.475      263145.181     2094746.475      264030.997
     2095238.595      264621.541     2095238.595      266097.901
     2095533.867      266590.021     2095435.443      266983.717
     2095632.291      267082.141     2095632.291      267278.989
     2095533.867      267475.837     2094549.627      267278.989
     2094352.779      267377.413     2094254.355      267672.685
     2093860.659      267672.685     2093466.963      268066.381
     2093598.013      269181.307     2093270.115      269542.741
     2092409.043      269616.421     2092272.003      269906.017

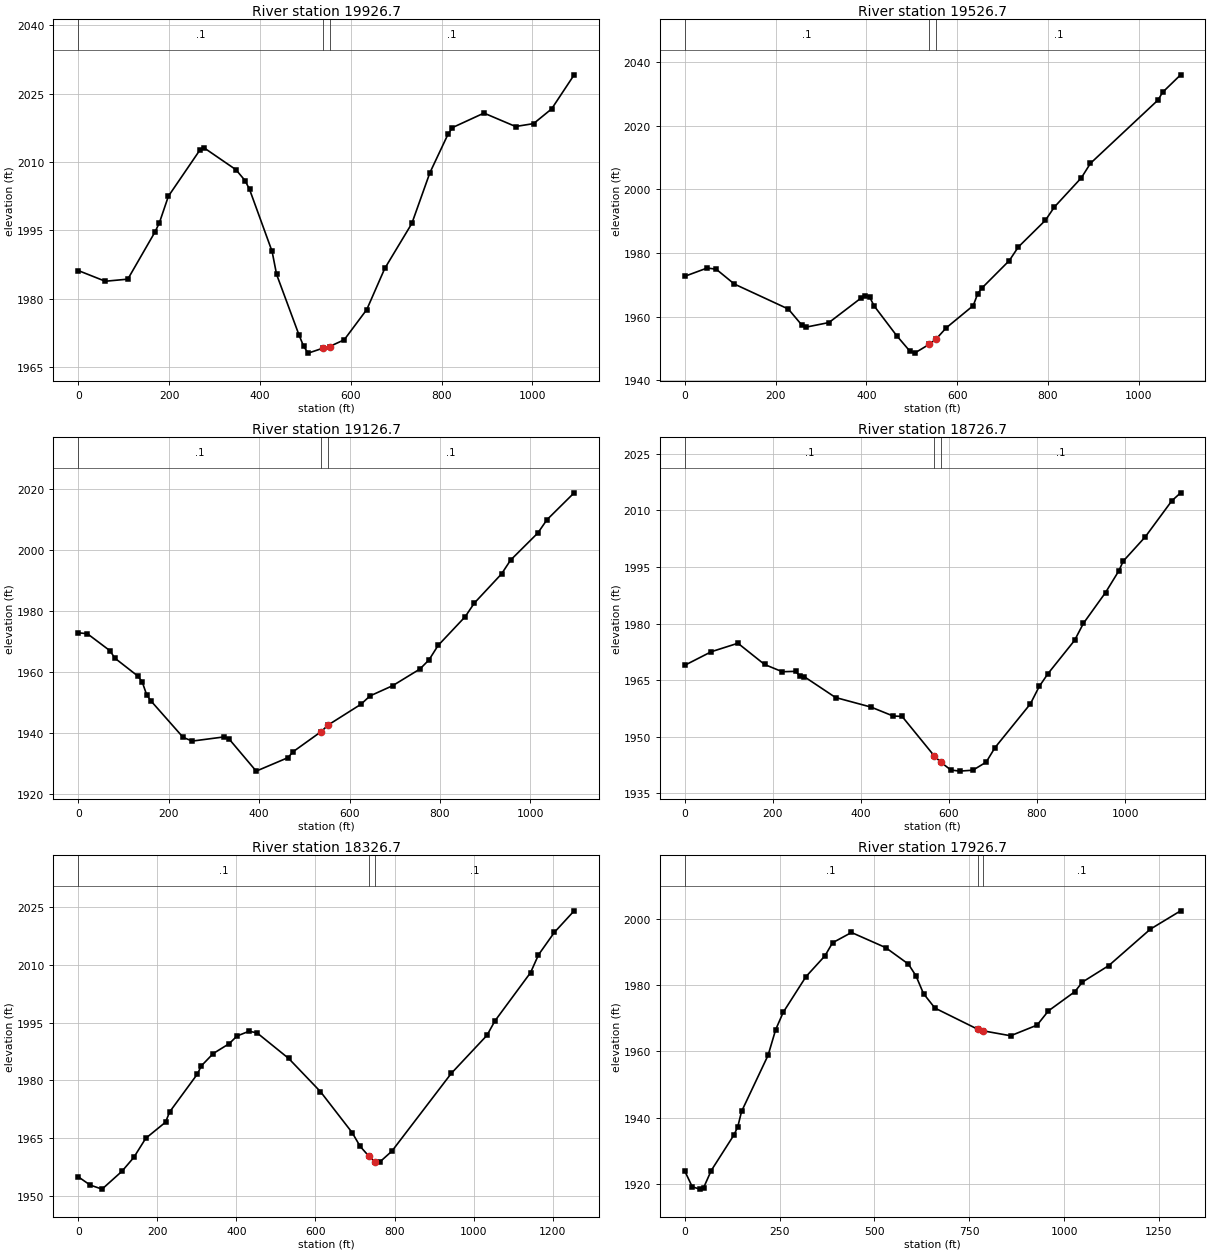
Type RM Length L Ch R = 1 ,19926.7,400,400,400
XS GIS Cut Line= 3
     2096464.227      256317.287     2097010.227      256317.287
     2097556.227      256317.287
#Sta/Elev= 30
       0 1986.19    59.6 1983.84   109.2 1984.30   168.8 1994.60   178.7 1996.65
   198.6 2002.49   268.0 2012.62   278.0 2013.03   347.4 2008.29   367.3 2005.92
   377.2 2004.00   426.9 1990.38   436.8 1985.34   486.4 1972.00   496.4 1969.57
   506.3 1968.08   538.5 1969.15   553.5 1969.53   585.7 1971.00   635.4 1977.64
   675.0 1986.65   734.6 1996.51   774.3 2007.62   814.0 2016.02   824.0 2017.53
   893.4 2020.71   963.0 2017.77  1002.6 2018.40  1042.4 2021.63  1092.0 2029.10
#Mann= 3 , 0 , 0
       0     0.1       0   538.5   0.045       0   553.5     0.1       0
Bank Sta=   538.5,   553.5
Exp/Cntr=0.3,0.1

Type RM Length L Ch R = 1 ,19526.7,400,400,397.1
XS GIS Cut Line= 3
     2096464.227      256717.287     2097010.227      256717.287
     2097556.227      256717.287
#Sta/Elev= 30
       0 1972.67    49.6 1975.29    69.5 1974.90   109.2 1970.26   228.3 1962.39
   258.1 1957.33   268.0 1956.73   317.7 1958.15   387.2 1965.72   397.1 1966.59
   407.0 1966.24   417.0 1963.40   466.6 1954.06   496.4 1949.07   506.3 1948.54
   538.5 1951.32   553.5 1952.95   575.8 1956.47   635.4 1963.47   645.3 1967.26
   655.2 1969.09   714.8 1977.62   734.6 1981.88   794.2 1990.27   814.0 1994.44
   873.6 2003.66   893.4 2008.17  1042.4 2028.09  1052.3 2030.50  1092.0 2035.99
#Mann= 3 , 0 , 0
       0     0.1       0   538.5   0.045       0   553.5     0.1       0
Bank Sta=   538.5,   553.5
Exp/Cntr=0.3,0.1

Type RM Length L Ch R = 1 ,19126.7,411.4,400,388.5
XS GIS Cut Line= 3
     2096465.227      257117.287     2097010.227      257117.287
     2097557.219      257045.611
#Sta/Elev= 30
       0 1972.80    20.2 1972.49    70.6 1966.88    80.7 1964.53   131.2 1958.70
   141.3 1956.82   151.4 1952.48   161.5 1950.38   232.1 1938.54   252.3 1937.35
   323.0 1938.72   333.1 1938.12   393.6 1927.51   464.3 1931.95   474.4 1933.78
   537.5 1940.47   552.5 1942.59   625.2 1949.39   645.3 1952.13   695.4 1955.48
   755.6 1960.93   775.7 1963.92   795.8 1968.64   855.9 1978.09   876.0 1982.53
   936.2 1992.08   956.2 1996.60  1016.4 2005.46  1036.5 2009.79  1096.7 2018.61
#Mann= 3 , 0 , 0
       0     0.1       0   537.5   0.045       0   552.5     0.1       0
Bank Sta=   537.5,   552.5
Exp/Cntr=0.3,0.1

Type RM Length L Ch R = 1 ,18726.7,388.4,400,395.8
XS GIS Cut Line= 3
     2096626.258      257727.349     2097136.885      257464.824
     2097591.472      257151.897
#Sta/Elev= 30
       0 1968.94    60.4 1972.54   120.9 1974.79   181.3 1969.17   221.6 1967.24
   251.8 1967.34   261.9 1966.05   272.0 1965.89   342.5 1960.41   423.1 1957.87
   473.4 1955.50   493.6 1955.40   566.7 1944.93   581.7 1943.25   604.3 1941.20
   624.3 1940.90   654.4 1941.15   684.5 1943.28   704.6 1947.14   784.9 1958.72
   805.0 1963.34   825.0 1966.76   885.2 1975.54   905.3 1980.06   955.5 1988.22
   985.6 1993.95   995.6 1996.53  1045.8 2002.99  1106.0 2012.53  1126.0 2014.65
#Mann= 3 , 0 , 0
       0     0.1       0   566.7   0.045       0   581.7     0.1       0
Bank Sta=   566.7,   581.7
Exp/Cntr=0.3,0.1

Type RM Length L Ch R = 1 ,18326.7,395.2,400,428.3
XS GIS Cut Line= 3
     2096679.410      257813.770     2097419.728      257747.666
     2097781.193      257386.201
#Sta/Elev= 30
       0 1954.96    30.1 1952.81    60.3 1951.75   110.5 1956.37   140.6 1959.98
   170.8 1964.94   221.0 1969.14   231.0 1971.76   301.3 1981.61   311.4 1983.75
   341.5 1986.95   381.7 1989.50   401.8 1991.51   431.9 1992.73   452.0 1992.34
   532.3 1985.68   612.7 1977.06   693.0 1966.41   713.1 1962.85   735.8 1960.23
   750.8 1958.75   763.3 1958.84   793.4 1961.61   943.7 1981.81  1033.9 1991.68
  1054.0 1995.42  1144.2 2007.97  1164.2 2012.58  1204.3 2018.40  1254.4 2024.00
#Mann= 3 , 0 , 0
       0     0.1       0   735.8   0.045       0   750.8     0.1       0
Bank Sta=   735.8,   750.8
Exp/Cntr=0.3,0.1

Type RM Length L Ch R = 1 ,17926.7,390.5,400,390.4
XS GIS Cut Line= 3
     2096683.867      257903.897     2097441.316      258088.165
     2097926.431      258296.064
#Sta/Elev= 30
       0 1924.01    20.0 1919.20    40.0 1918.50    50.0 1918.95    70.0 1924.11
   129.9 1934.84   139.9 1937.28   149.9 1941.90   219.9 1958.86   239.9 1966.59
   259.8 1971.81   319.8 1982.56   369.8 1988.83   389.8 1992.76   439.7 1995.86
   529.7 1991.31   589.6 1986.35   609.6 1982.81   629.6 1977.43   659.6 1973.08
     772 1966.72     787 1966.21   859.2 1964.73   928.9 1967.94   958.8 1972.23
  1028.5 1978.02  1048.4 1980.91  1118.1 1985.90  1227.7 1996.88  1307.3 2002.39
#Mann= 3 , 0 , 0
       0     0.1       0     772   0.045       0     787     0.1       0
Bank Sta=     772,     787
Exp/Cntr=0.3,0.1

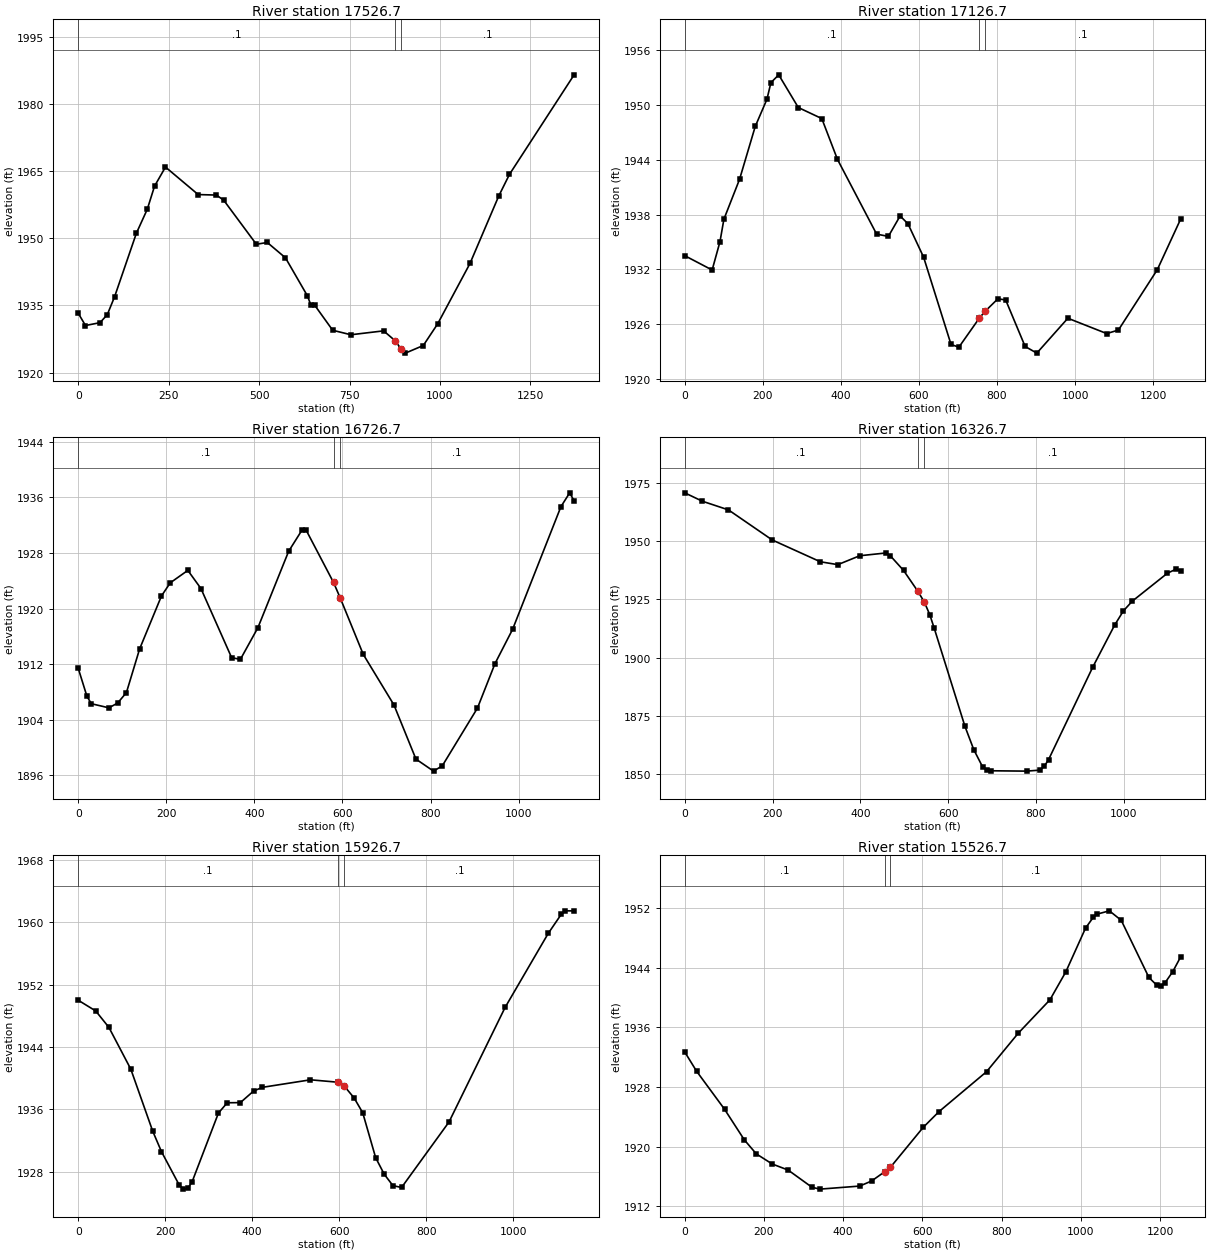
Type RM Length L Ch R = 1 ,17526.7,396.7,400,437.3
XS GIS Cut Line= 3
     2096659.051      257995.993     2097403.923      258472.676
     2097890.215      258472.676
#Sta/Elev= 30
       0 1933.28    20.1 1930.53    60.3 1931.17    80.4 1932.96   100.5 1936.94
   160.8 1951.13   190.9 1956.47   211.0 1961.63   241.2 1965.89   331.6 1959.75
   381.9 1959.64   402.0 1958.51   492.4 1948.66   522.6 1949.06   572.8 1945.64
   633.1 1937.21   643.2 1935.10   653.2 1935.11   703.4 1929.47   753.7 1928.47
   844.1 1929.34   876.8 1927.08   891.8 1925.34   904.2 1924.37   953.8 1926.07
   993.5 1930.90  1082.8 1944.37  1162.2 1959.40  1192.0 1964.26  1370.6 1986.47
#Mann= 3 , 0 , 0
       0     0.1       0   876.8   0.045       0   891.8     0.1       0
Bank Sta=   876.8,   891.8
Exp/Cntr=0.3,0.1

Type RM Length L Ch R = 1 ,17126.7,388.5,400,400
XS GIS Cut Line= 2
     2096590.464      258042.891     2097091.269      258617.677
#Sta/Elev= 30
       0 1933.50    70.2 1931.93    90.3 1935.04   100.3 1937.49   140.4 1941.86
   180.6 1947.65   210.6 1950.63   220.7 1952.44   240.7 1953.30   290.9 1949.72
   351.1 1948.51   391.2 1944.04   491.5 1935.86   521.6 1935.61   551.7 1937.85
   571.8 1936.99   611.9 1933.33   682.1 1923.78   702.2 1923.48   754.9 1926.68
   769.9 1927.43   802.2 1928.78   822.1 1928.65   871.9 1923.56   901.8 1922.83
   981.4 1926.65  1081.0 1924.97  1110.9 1925.36  1210.4 1931.96  1270.2 1937.50
#Mann= 3 , 0 , 0
       0     0.1       0   754.9   0.045       0   769.9     0.1       0
Bank Sta=   754.9,   769.9
Exp/Cntr=0.3,0.1

Type RM Length L Ch R = 1 ,16726.7,410.6,400,389.8
XS GIS Cut Line= 2
     2096493.086      258064.815     2096691.269      258617.677
#Sta/Elev= 30
       0 1911.41    19.9 1907.36    29.9 1906.31    69.7 1905.72    89.6 1906.41
   109.5 1907.92   139.4 1914.18   189.1 1921.81   209.0 1923.69   248.9 1925.48
   278.7 1922.87   348.4 1912.93   368.3 1912.69   408.1 1917.25   477.8 1928.22
   507.7 1931.23   517.6 1931.26   579.8 1923.74   594.8 1921.54   647.2 1913.41
   717.0 1906.13   766.9 1898.35   806.8 1896.62   826.7 1897.38   906.6 1905.69
   946.4 1912.08   986.4 1917.01  1096.1 1934.64  1116.0 1936.63  1126.0 1935.48
#Mann= 3 , 0 , 0
       0     0.1       0   579.8   0.045       0   594.8     0.1       0
Bank Sta=   579.8,   594.8
Exp/Cntr=0.3,0.1

Type RM Length L Ch R = 1 ,16326.7,390.3,400,391.5
XS GIS Cut Line= 3
     2095919.620      258258.451     2096300.053      258638.884
     2096544.358      259177.313
#Sta/Elev= 30
       0 1970.79    39.8 1967.21    99.6 1963.46   199.3 1950.55   308.9 1941.19
   348.7 1939.96   398.5 1943.78   458.3 1944.97   468.3 1943.74   498.2 1937.51
   530.5 1928.63   545.5 1923.96   558.1 1918.44   568.1 1912.70   638.2 1870.50
   658.3 1860.51   678.3 1853.16   688.3 1851.68   698.4 1851.47   778.5 1851.32
   808.6 1851.75   818.6 1853.33   828.6 1856.28   928.8 1895.82   979.0 1914.00
   999.0 1920.10  1019.0 1924.25  1099.2 1936.28  1119.2 1938.05  1129.3 1937.24
#Mann= 3 , 0 , 0
       0     0.1       0   530.5   0.045       0   545.5     0.1       0
Bank Sta=   530.5,   545.5
Exp/Cntr=0.3,0.1

Type RM Length L Ch R = 1 ,15926.7,391,400,396.1
XS GIS Cut Line= 3
     2095793.357      258359.955     2096017.210      258921.726
     2096395.962      259300.478
#Sta/Elev= 30
       0 1950.01    40.3 1948.63    70.6 1946.52   121.0 1941.15   171.3 1933.20
   191.5 1930.56   231.8 1926.33   241.9 1925.75   252.0 1925.84   262.0 1926.70
   322.5 1935.52   342.7 1936.84   372.9 1936.86   403.2 1938.34   423.3 1938.82
   534.2 1939.79   597.2 1939.48   612.2 1938.96   634.5 1937.46   654.3 1935.56
   684.1 1929.78   703.9 1927.65   723.8 1926.20   743.6 1925.96   852.7 1934.37
   981.7 1949.08  1080.8 1958.58  1110.6 1961.02  1120.5 1961.49  1140.4 1961.48
#Mann= 3 , 0 , 0
       0     0.1       0   597.2   0.045       0   612.2     0.1       0
Bank Sta=   597.2,   612.2
Exp/Cntr=0.3,0.1

Type RM Length L Ch R = 1 ,15526.7,428.8,400,395.9
XS GIS Cut Line= 2
     2095695.112      258401.155     2096218.516      259435.822
#Sta/Elev= 30
       0 1932.70    30.1 1930.10   100.4 1925.02   150.5 1920.90   180.6 1919.03
   220.8 1917.67   260.9 1916.86   321.1 1914.55   341.2 1914.30   441.6 1914.71
   471.6 1915.39   504.3 1916.62   519.3 1917.24   601.8 1922.58   641.8 1924.70
   761.7 1930.05   841.7 1935.21   921.7 1939.69   961.7 1943.43  1011.7 1949.32
  1031.7 1950.80  1041.7 1951.20  1071.7 1951.63  1101.7 1950.36  1171.6 1942.69
  1191.6 1941.64  1201.6 1941.57  1211.6 1941.93  1231.6 1943.46  1251.6 1945.44
#Mann= 3 , 0 , 0
       0     0.1       0   504.3   0.045       0   519.3     0.1       0
Bank Sta=   504.3,   519.3
Exp/Cntr=0.3,0.1

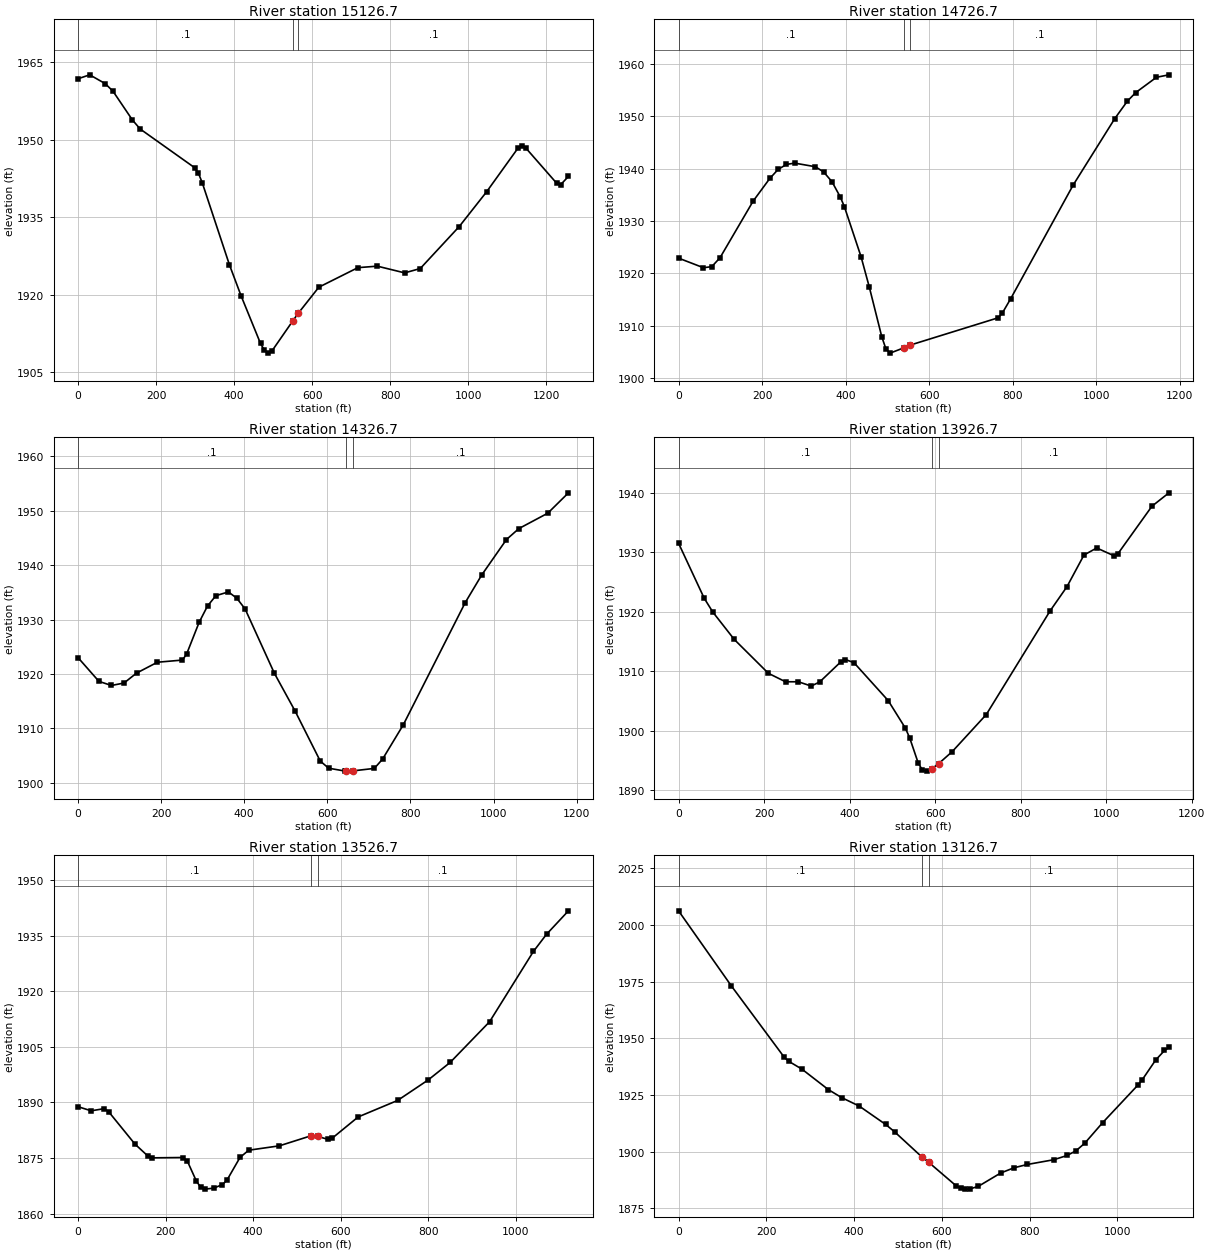
Type RM Length L Ch R = 1 ,15126.7,414.7,400,384.1
XS GIS Cut Line= 3
     2095011.611      259012.368     2095533.062      259209.027
     2096165.005      259509.654
#Sta/Elev= 30
       0 1961.82    29.9 1962.58    69.7 1960.87    89.6 1959.40   139.3 1953.84
   159.2 1952.09   298.6 1944.61   308.5 1943.54   318.5 1941.65   388.1 1925.78
   418.0 1919.77   467.7 1910.56   477.7 1909.24   487.6 1908.69   497.6 1909.17
   549.8 1914.86   564.8 1916.44   617.3 1921.46   717.3 1925.24   767.2 1925.53
   837.2 1924.23   877.2 1925.07   977.2 1933.21  1047.2 1939.92  1127.1 1948.32
  1137.1 1948.77  1147.1 1948.47  1227.1 1941.57  1237.1 1941.31  1257.1 1942.91
#Mann= 3 , 0 , 0
       0     0.1       0   549.8   0.045       0   564.8     0.1       0
Bank Sta=   549.8,   564.8
Exp/Cntr=0.3,0.1

Type RM Length L Ch R = 1 ,14726.7,390.4,400,398.2
XS GIS Cut Line= 3
     2094997.399      259631.023     2095533.867      259527.823
     2096158.145      259597.471
#Sta/Elev= 30
       0 1922.92    59.6 1921.09    79.5 1921.29    99.3 1922.99   178.8 1933.82
   218.5 1938.12   238.4 1939.84   258.2 1940.80   278.1 1941.05   327.8 1940.36
   347.6 1939.35   367.5 1937.50   387.4 1934.58   397.3 1932.71   437.0 1923.21
   456.9 1917.38   486.7 1907.91   496.6 1905.60   506.6 1904.79   538.8 1905.78
   553.8 1906.30   765.7 1911.54   775.6 1912.46   795.6 1915.20   945.1 1936.87
  1044.8 1949.56  1074.8 1952.87  1094.7 1954.50  1144.5 1957.43  1174.4 1957.90
#Mann= 3 , 0 , 0
       0     0.1       0   538.8   0.045       0   553.8     0.1       0
Bank Sta=   538.8,   553.8
Exp/Cntr=0.3,0.1

Type RM Length L Ch R = 1 ,14326.7,389.7,400,400.3
XS GIS Cut Line= 3
     2094996.416      259736.749     2095632.291      259887.054
     2096158.985      259904.297
#Sta/Elev= 30
       0 1922.99    50.3 1918.63    80.4 1917.88   110.6 1918.33   140.7 1920.15
   191.0 1922.15   251.3 1922.55   261.4 1923.67   291.5 1929.50   311.6 1932.48
   331.7 1934.38   361.9 1935.07   382.0 1933.92   402.1 1931.94   472.5 1920.13
   522.7 1913.14   583.0 1903.99   603.1 1902.68   643.4 1902.14   645.9 1902.14
   660.9 1902.18   713.1 1902.64   732.9 1904.34   782.7 1910.63   931.8 1933.09
   971.6 1938.18  1031.2 1944.70  1061.1 1946.71  1130.7 1949.54  1180.4 1953.28
#Mann= 3 , 0 , 0
       0     0.1       0   645.9   0.045       0   660.9     0.1       0
Bank Sta=   645.9,   660.9
Exp/Cntr=0.3,0.1

Type RM Length L Ch R = 1 ,13926.7,409.7,400,392.6
XS GIS Cut Line= 3
     2094945.460      259827.810     2095422.387      260192.461
     2095930.496      260393.187
#Sta/Elev= 30
       0 1931.56    60.0 1922.31    80.0 1920.00   130.1 1915.40   210.1 1909.69
   250.2 1908.27   280.2 1908.27   310.2 1907.55   330.2 1908.25   380.2 1911.67
   390.2 1912.01   410.2 1911.48   490.3 1905.10   530.3 1900.49   540.3 1898.88
   560.3 1894.64   570.3 1893.40   580.4 1893.25   592.9 1893.68   607.9 1894.49
   640.1 1896.54   719.6 1902.76   868.6 1920.16   908.3 1924.26   948.0 1929.57
   977.8 1930.76  1017.6 1929.47  1027.5 1929.80  1107.0 1937.78  1146.7 1940.03
#Mann= 3 , 0 , 0
       0     0.1       0   592.9   0.045       0   607.9     0.1       0
Bank Sta=   592.9,   607.9
Exp/Cntr=0.3,0.1

Type RM Length L Ch R = 1 ,13526.7,406,400,395.4
XS GIS Cut Line= 3
     2094797.097      260507.093     2095337.019      260507.093
     2095917.299      260493.453
#Sta/Elev= 30
       0 1888.82    30.0 1887.71    60.0 1888.30    70.0 1887.45   130.0 1878.73
   160.0 1875.46   170.0 1875.02   240.0 1875.11   250.0 1874.06   270.0 1868.83
   280.0 1867.08   290.0 1866.58   310.0 1866.85   330.0 1867.82   340.0 1868.96
   370.0 1875.13   389.9 1877.08   459.9 1878.26   532.4 1880.98   547.4 1880.81
   570.0 1880.04   580.0 1880.26   640.0 1886.06   730.1 1890.51   800.1 1896.05
   850.2 1900.77   940.2 1911.74  1040.3 1930.70  1070.3 1935.34  1120.4 1941.67
#Mann= 3 , 0 , 0
       0     0.1       0   532.4   0.045       0   547.4     0.1       0
Bank Sta=   532.4,   547.4
Exp/Cntr=0.3,0.1

Type RM Length L Ch R = 1 ,13126.7,385.5,400,409.4
XS GIS Cut Line= 3
     2094892.372      261011.922     2095435.443      260866.325
     2095976.393      260742.402
#Sta/Elev= 30
       0 2006.22   120.5 1973.05   241.0 1941.57   251.0 1939.84   281.1 1936.38
   341.4 1927.34   371.5 1923.83   411.6 1920.09   471.9 1911.97   492.0 1908.77
   554.8 1897.57   569.8 1895.29   632.9 1884.83   643.0 1883.87   653.1 1883.45
   663.2 1883.48   683.3 1884.72   733.8 1890.55   764.0 1892.85   794.3 1894.32
   854.9 1896.42   885.1 1898.29   905.3 1900.34   925.5 1903.72   965.9 1912.71
  1046.6 1929.36  1056.7 1931.79  1086.9 1940.38  1107.1 1944.61  1117.2 1945.96
#Mann= 3 , 0 , 0
       0     0.1       0   554.8   0.045       0   569.8     0.1       0
Bank Sta=   554.8,   569.8
Exp/Cntr=0.3,0.1

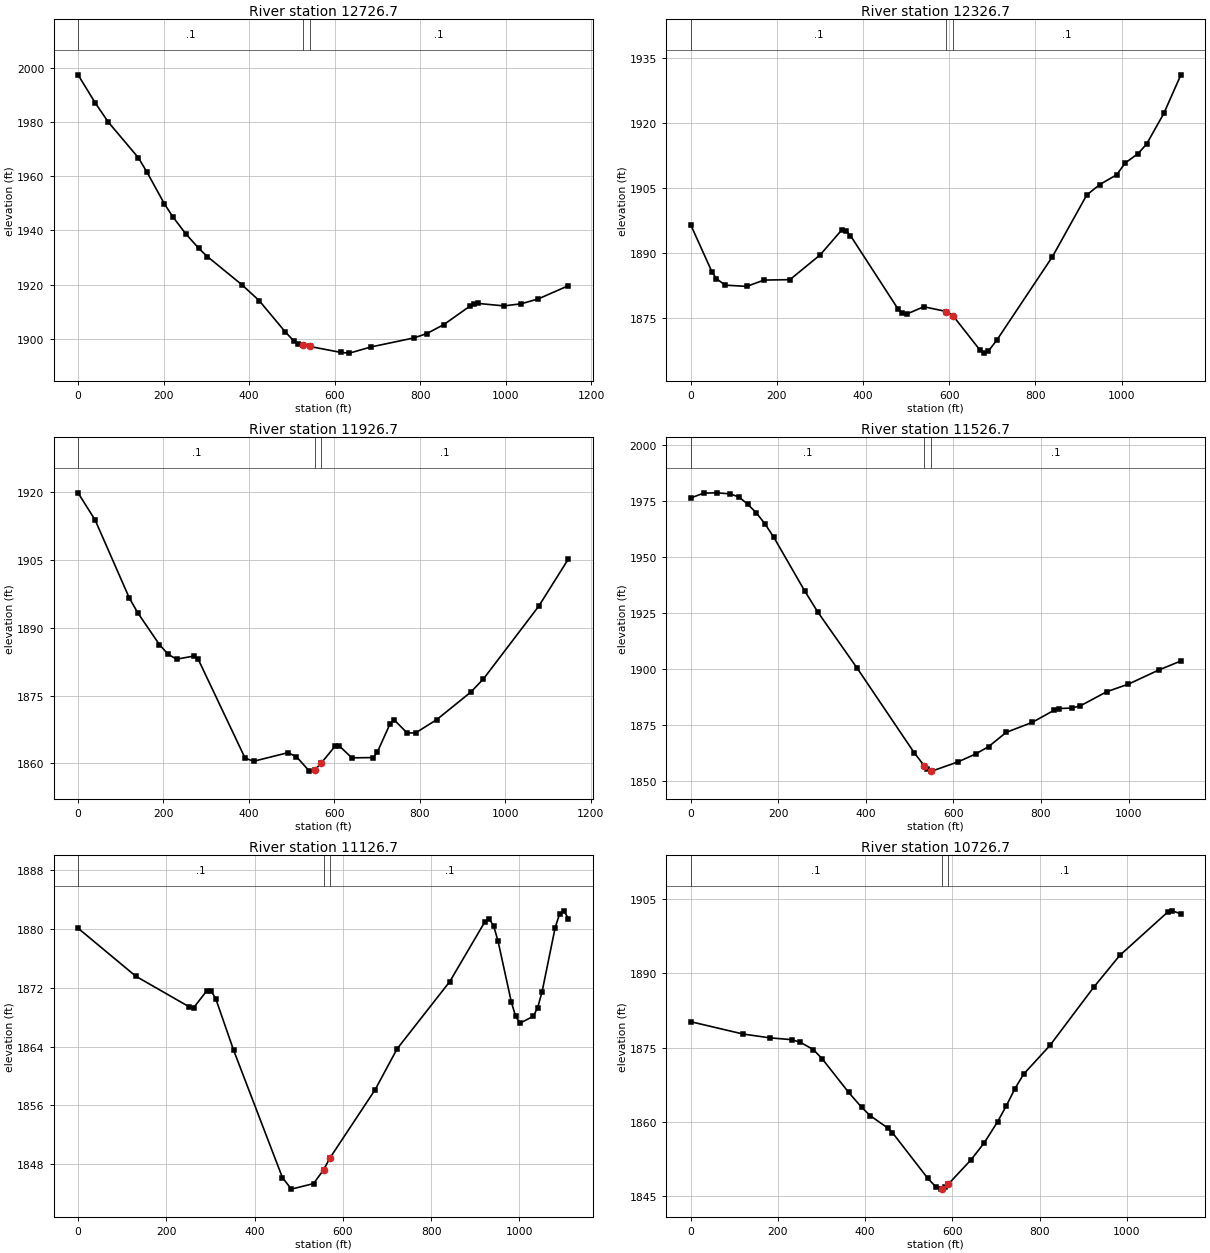
Type RM Length L Ch R = 1 ,12726.7,402.4,400,397.6
XS GIS Cut Line= 3
     2094901.551      261167.310     2095435.443      261184.788
     2096044.316      261249.258
#Sta/Elev= 30
       0 1997.31    40.3 1986.93    70.6 1979.91   141.1 1966.73   161.3 1961.39
   201.6 1949.84   221.7 1944.94   252.0 1938.68   282.2 1933.36   302.4 1930.32
   383.0 1919.94   423.3 1914.12   483.8 1902.68   503.9 1899.32   514.0 1898.24
   526.7 1897.62   541.7 1897.19   614.5 1894.99   634.6 1894.73   684.7 1897.00
   785.1 1900.33   815.2 1901.92   855.4 1905.27   915.6 1911.99   925.6 1912.77
   935.7 1913.04   995.9 1912.14  1036.0 1912.91  1076.2 1914.73  1146.4 1919.58
#Mann= 3 , 0 , 0
       0     0.1       0   526.7   0.045       0   541.7     0.1       0
Bank Sta=   526.7,   541.7
Exp/Cntr=0.3,0.1

Type RM Length L Ch R = 1 ,12326.7,398,400,417.4
XS GIS Cut Line= 3
     2094934.205      261587.660     2095533.867      261544.019
     2096070.117      261544.019
#Sta/Elev= 30
       0 1896.56    50.1 1885.51    60.1 1884.05    80.2 1882.55   130.3 1882.26
   170.4 1883.72   230.5 1883.82   300.6 1889.54   350.7 1895.30   360.8 1895.13
   370.8 1894.01   481.0 1877.09   491.0 1876.00   501.0 1875.85   541.1 1877.56
   593.7 1876.45   608.7 1875.50   670.8 1867.62   680.7 1866.84   690.6 1867.27
   710.5 1869.85   839.6 1889.15   919.0 1903.36   948.8 1905.77   988.5 1908.05
  1008.4 1910.78  1038.2 1912.96  1058.0 1915.16  1097.8 1922.22  1137.5 1931.15
#Mann= 3 , 0 , 0
       0     0.1       0   593.7   0.045       0   608.7     0.1       0
Bank Sta=   593.7,   608.7
Exp/Cntr=0.3,0.1

Type RM Length L Ch R = 1 ,11926.7,386.1,400,388.1
XS GIS Cut Line= 3
     2094923.957      261684.650     2095455.517      261865.669
     2095863.048      262287.342
#Sta/Elev= 30
       0 1919.87    40.1 1913.82   120.3 1896.52   140.4 1893.22   190.5 1886.27
   210.6 1884.15   230.6 1883.04   270.7 1883.73   280.8 1883.13   391.1 1861.13
   411.1 1860.45   491.4 1862.34   511.4 1861.45   541.5 1858.26     554 1858.48
     569 1860.00   601.3 1863.73   611.2 1863.89   641.0 1861.20   690.8 1861.26
   700.7 1862.46   730.5 1868.75   740.4 1869.58   770.3 1866.72   790.1 1866.71
   839.8 1869.66   919.4 1875.74   949.2 1878.68  1078.4 1894.74  1148.0 1905.22
#Mann= 3 , 0 , 0
       0     0.1       0     554   0.045       0     569     0.1       0
Bank Sta=     554,     569
Exp/Cntr=0.3,0.1

Type RM Length L Ch R = 1 ,11526.7,395.2,400,404.5
XS GIS Cut Line= 3
     2094732.444      261973.556     2095238.595      262164.058
     2095754.692      262425.550
#Sta/Elev= 30
       0 1976.23    30.0 1978.44    60.1 1978.56    90.1 1978.10   110.2 1976.73
   130.2 1973.53   150.2 1969.62   170.3 1964.60   190.3 1958.65   260.4 1934.88
   290.4 1925.43   380.6 1900.32   510.8 1862.63   533.3 1856.96   540.8 1855.42
   548.3 1854.74   550.8 1854.51   610.6 1858.64   650.5 1862.12   680.5 1865.45
   720.4 1871.76   780.2 1876.26   830.1 1881.67   840.1 1882.40   870.0 1882.62
   890.0 1883.62   949.8 1889.88   999.7 1893.30  1069.5 1899.64  1119.4 1903.61
#Mann= 3 , 0 , 0
       0     0.1       0   533.3   0.045       0   548.3     0.1       0
Bank Sta=   533.3,   548.3
Exp/Cntr=0.3,0.1

Type RM Length L Ch R = 1 ,11126.7,405.1,400,389.3
XS GIS Cut Line= 3
     2094612.792      262208.033     2095092.741      262503.643
     2095523.614      262840.970
#Sta/Elev= 30
       0 1880.07   130.8 1873.55   251.6 1869.40   261.7 1869.25   291.9 1871.59
   302.0 1871.50   312.0 1870.49   352.3 1863.52   463.0 1846.20   483.2 1844.63
   533.5 1845.38   556.2 1847.25   571.2 1848.91   673.1 1858.14   722.9 1863.69
   842.3 1872.83   921.9 1880.96   931.8 1881.31   941.8 1880.34   951.7 1878.27
   981.6 1870.05   991.5 1868.09  1001.4 1867.18  1031.3 1868.10  1041.2 1869.26
  1051.2 1871.41  1081.0 1880.16  1091.0 1882.01  1100.9 1882.43  1110.9 1881.37
#Mann= 3 , 0 , 0
       0     0.1       0   556.2   0.045       0   571.2     0.1       0
Bank Sta=   556.2,   571.2
Exp/Cntr=0.3,0.1

Type RM Length L Ch R = 1 ,10726.7,408.2,400,402.4
XS GIS Cut Line= 3
     2094395.265      262641.618     2094943.323      262841.752
     2095469.773      262964.503
#Sta/Elev= 30
       0 1880.22   120.7 1877.72   181.1 1876.96   231.4 1876.59   251.5 1876.07
   281.7 1874.56   301.8 1872.71   362.2 1865.96   392.3 1862.90   412.4 1861.20
   452.7 1858.70   462.7 1857.81   543.2 1848.64   563.3 1846.75   573.4 1846.40
     576 1846.49   583.5 1846.76     591 1847.43   643.5 1852.38   673.6 1855.81
   703.6 1859.98   723.6 1863.19   743.6 1866.71   763.6 1869.64   823.7 1875.41
   923.8 1887.14   983.9 1893.61  1094.0 1902.38  1104.0 1902.61  1124.0 1902.00
#Mann= 3 , 0 , 0
       0     0.1       0     576   0.045       0     591     0.1       0
Bank Sta=     576,     591
Exp/Cntr=0.3,0.1

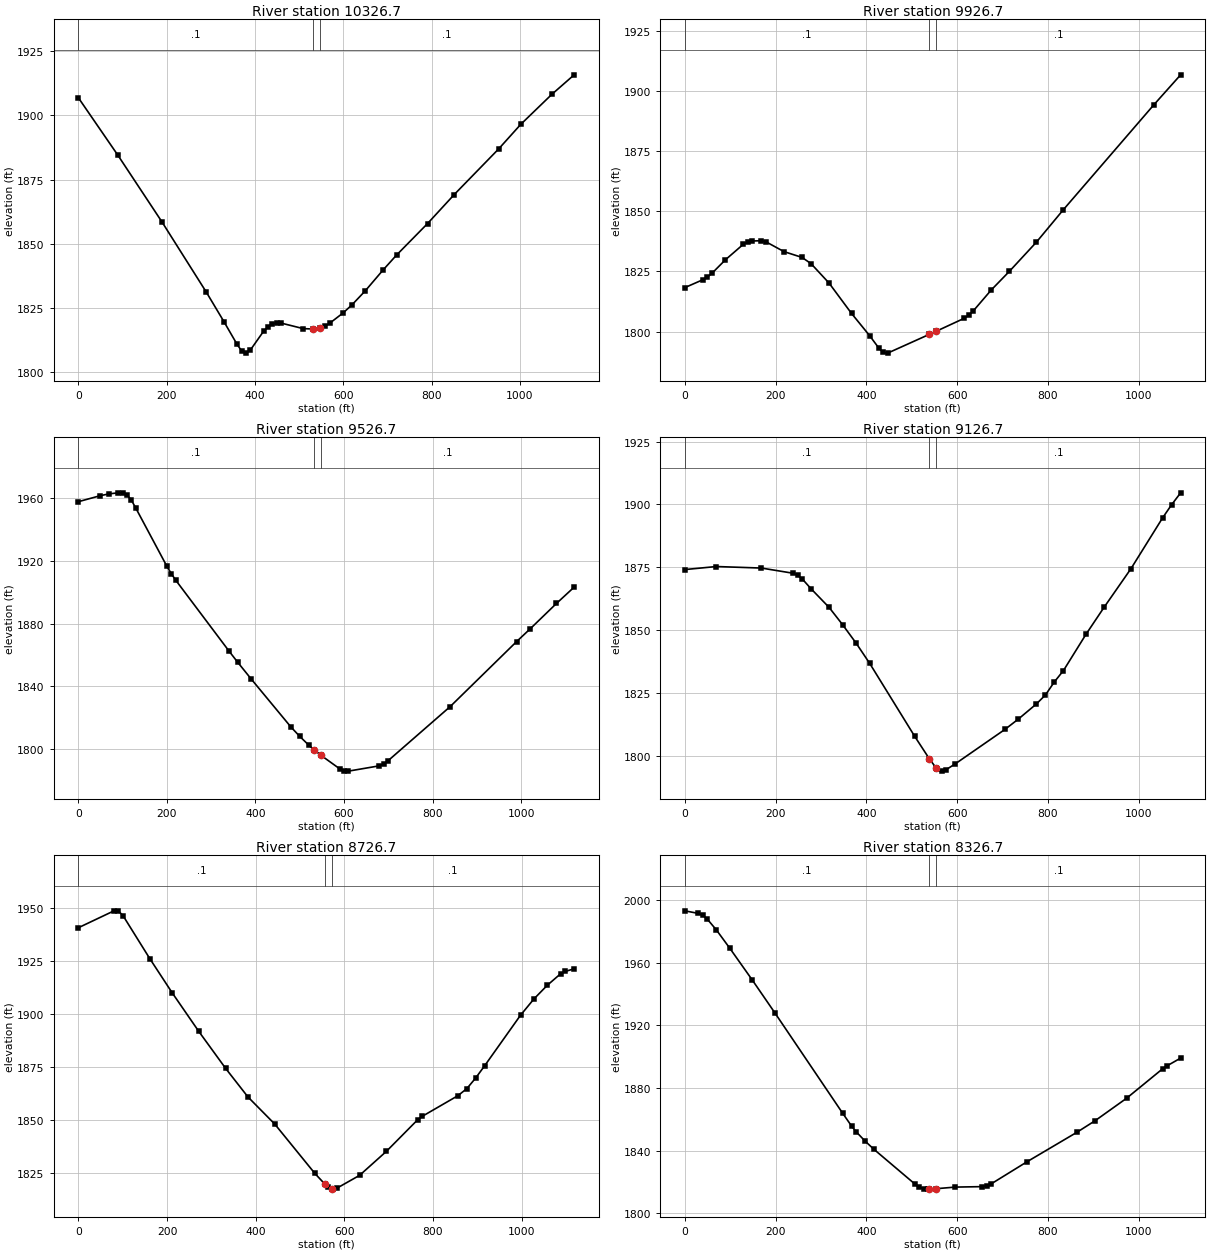
Type RM Length L Ch R = 1 ,10326.7,400,400,392.3
XS GIS Cut Line= 3
     2094207.083      263160.215     2094746.475      263160.215
     2095298.729      263348.423
#Sta/Elev= 30
       0 1906.92    89.9 1884.41   189.8 1858.39   289.7 1831.16   329.6 1819.66
   359.6 1810.73   369.6 1808.26   379.6 1807.35   389.6 1808.56   419.5 1815.88
   429.5 1817.64   439.5 1818.74   449.5 1819.16   459.5 1819.05   509.4 1816.90
   531.9 1816.75   546.9 1817.11   559.5 1817.91   569.6 1819.05   599.8 1823.05
   619.9 1826.21   650.0 1831.68   690.3 1839.80   720.5 1845.56   790.9 1857.88
   851.2 1869.16   951.8 1886.95  1002.1 1896.57  1072.5 1908.27  1122.8 1915.84
#Mann= 3 , 0 , 0
       0     0.1       0   531.9   0.045       0   546.9     0.1       0
Bank Sta=   531.9,   546.9
Exp/Cntr=0.3,0.1

Type RM Length L Ch R = 1 ,9926.7,400,400,392.7
XS GIS Cut Line= 3
     2094200.475      263560.215     2094746.475      263560.215
     2095292.475      263560.215
#Sta/Elev= 30
       0 1818.28    39.7 1821.56    49.6 1822.67    59.6 1824.20    89.4 1829.85
   129.0 1836.32   139.0 1837.31   148.9 1837.68   168.8 1837.78   178.7 1837.34
   218.4 1833.26   258.1 1830.85   278.0 1828.26   317.7 1820.18   367.3 1807.53
   407.0 1798.33   426.9 1793.26   436.8 1791.33   446.7 1791.05   538.5 1798.85
   553.5 1800.12   615.5 1805.54   625.4 1806.84   635.4 1808.61   675.0 1817.32
   714.8 1825.04   774.3 1837.18   833.9 1850.72  1032.4 1894.16  1092.0 1906.76
#Mann= 3 , 0 , 0
       0     0.1       0   538.5   0.045       0   553.5     0.1       0
Bank Sta=   538.5,   553.5
Exp/Cntr=0.3,0.1

Type RM Length L Ch R = 1 ,9526.7,417.9,400,388.6
XS GIS Cut Line= 3
     2094206.443      263960.215     2094746.475      263960.215
     2095298.154      263781.765
#Sta/Elev= 30
       0 1957.52    50.0 1961.38    70.0 1962.52    90.0 1963.16   100.0 1963.11
   110.0 1961.86   120.0 1958.39   130.0 1953.35   200.0 1916.45   210.0 1911.72
   220.0 1907.59   340.0 1862.63   360.0 1855.38   390.0 1844.90   480.0 1814.28
   500.0 1808.28   520.0 1802.82   532.5 1799.70   547.5 1796.32   590.0 1787.70
   600.0 1786.40   610.0 1786.17   680.0 1789.55   690.0 1790.79   700.0 1792.90
   839.9 1827.24   989.9 1868.58  1019.9 1876.50  1079.9 1892.83  1119.8 1903.19
#Mann= 3 , 0 , 0
       0     0.1       0   532.5   0.045       0   547.5     0.1       0
Bank Sta=   532.5,   547.5
Exp/Cntr=0.3,0.1

Type RM Length L Ch R = 1 ,9126.7,392.1,400,406
XS GIS Cut Line= 3
     2094580.810      264637.577     2094979.267      264263.789
     2095365.305      263877.751
#Sta/Elev= 30
       0 1874.13    69.5 1875.34   168.9 1874.73   238.4 1872.68   248.3 1871.87
   258.3 1870.50   278.1 1866.51   317.9 1859.10   347.7 1852.22   377.5 1844.88
   407.3 1836.87   506.6 1807.84   538.8 1798.93   553.8 1795.30   556.3 1794.76
   566.2 1794.06   576.1 1794.68   596.0 1796.97   705.2 1810.62   734.9 1814.75
   774.6 1820.75   794.5 1824.32   814.4 1829.57   834.2 1834.02   883.8 1848.41
   923.5 1859.10   983.1 1874.54  1052.6 1894.68  1072.4 1899.88  1092.3 1904.62
#Mann= 3 , 0 , 0
       0     0.1       0   538.8   0.045       0   553.8     0.1       0
Bank Sta=   538.8,   553.8
Exp/Cntr=0.3,0.1

Type RM Length L Ch R = 1 ,8726.7,390,400,412.6
XS GIS Cut Line= 3
     2094677.513      264804.877     2095192.513      264575.460
     2095672.604      264297.773
#Sta/Elev= 30
       0 1940.71    80.5 1948.68    90.6 1948.56   100.7 1946.44   161.1 1926.20
   211.4 1910.16   271.8 1891.86   332.2 1874.49   382.6 1861.02   443.0 1848.26
   533.6 1824.98   556.3 1819.93   563.8 1818.42   571.3 1817.82   573.9 1817.61
   584.0 1818.15   634.4 1824.10   694.9 1835.41   765.5 1850.30   775.6 1851.88
   856.2 1861.62   876.4 1864.96   896.6 1870.04   916.7 1875.77   997.4 1899.51
  1027.6 1907.16  1057.9 1913.64  1088.2 1919.10  1098.2 1920.13  1118.4 1921.38
#Mann= 3 , 0 , 0
       0     0.1       0   556.3   0.045       0   571.3     0.1       0
Bank Sta=   556.3,   571.3
Exp/Cntr=0.3,0.1

Type RM Length L Ch R = 1 ,8326.7,400,400,400
XS GIS Cut Line= 3
     2094692.595      264956.372     2095238.595      264956.372
     2095784.595      264956.372
#Sta/Elev= 30
       0 1993.34    29.8 1991.70    39.7 1990.42    49.6 1988.00    69.5 1981.14
    99.3 1969.33   148.9 1948.97   198.6 1927.97   347.4 1863.98   367.3 1855.66
   377.2 1852.08   397.1 1846.02   417.0 1840.68   506.3 1818.69   516.2 1816.58
   526.2 1815.51   536.1 1815.32   538.5 1815.35   553.5 1815.59   595.6 1816.62
   655.2 1816.92   665.1 1817.41   675.0 1818.72   754.5 1832.97   863.7 1851.70
   903.4 1859.03   972.9 1873.43  1052.3 1892.28  1062.2 1894.21  1092.0 1899.13
#Mann= 3 , 0 , 0
       0     0.1       0   538.5   0.045       0   553.5     0.1       0
Bank Sta=   538.5,   553.5
Exp/Cntr=0.3,0.1