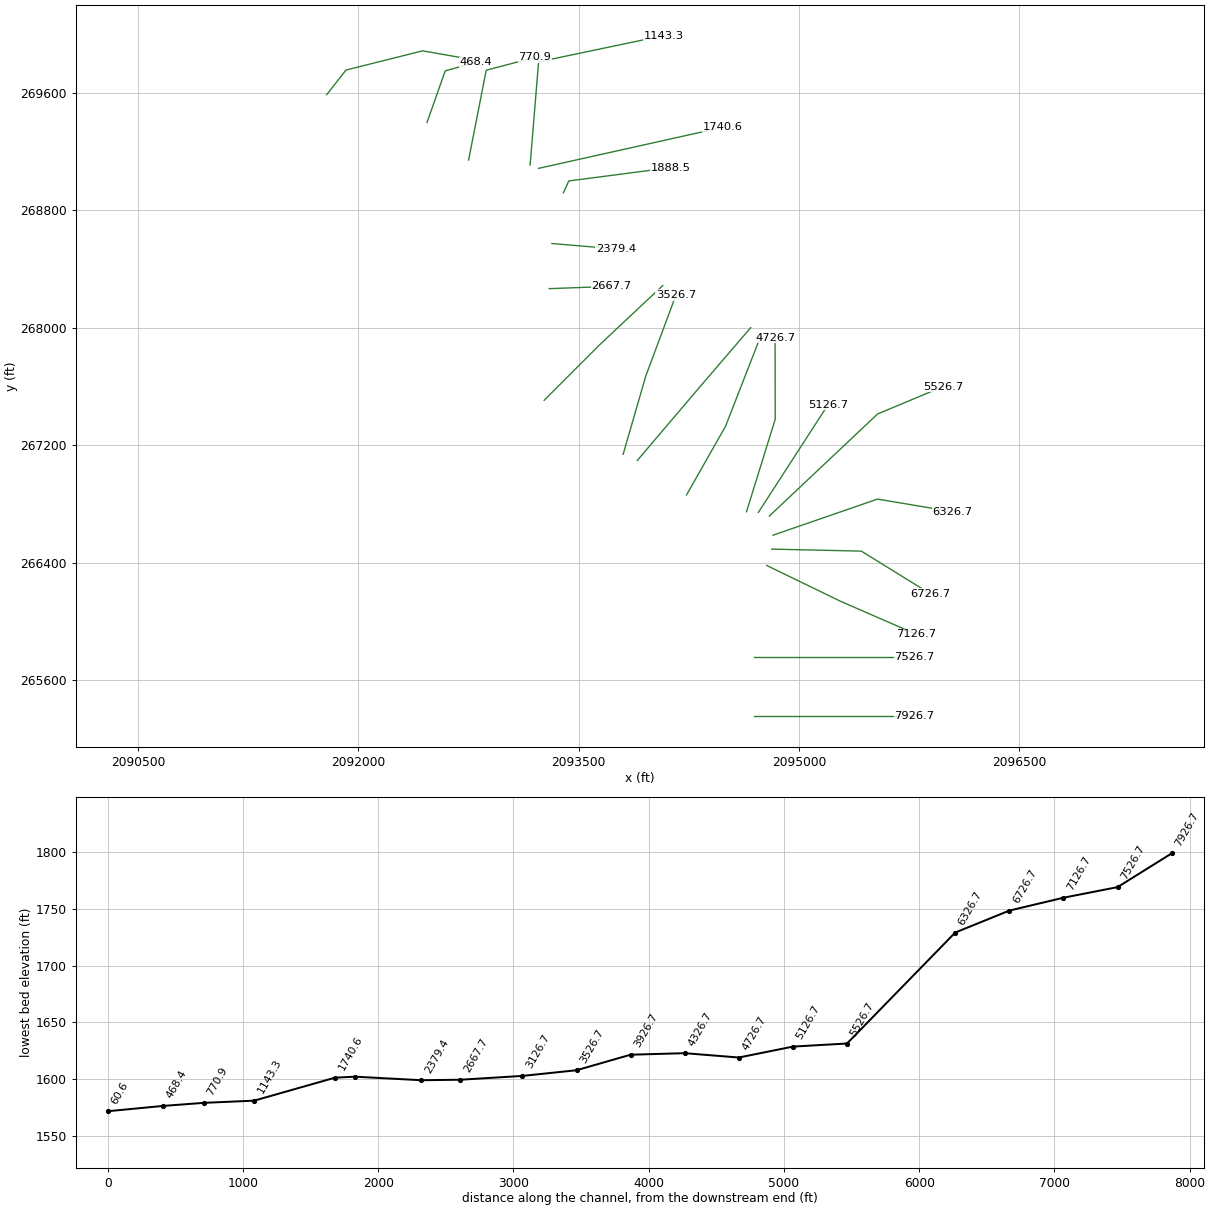
HEC-RAS study GrnbrRvT1.prj: GrnbrRvT1

--- GrnbrRvT1.g01 (geometry) --- (continued)

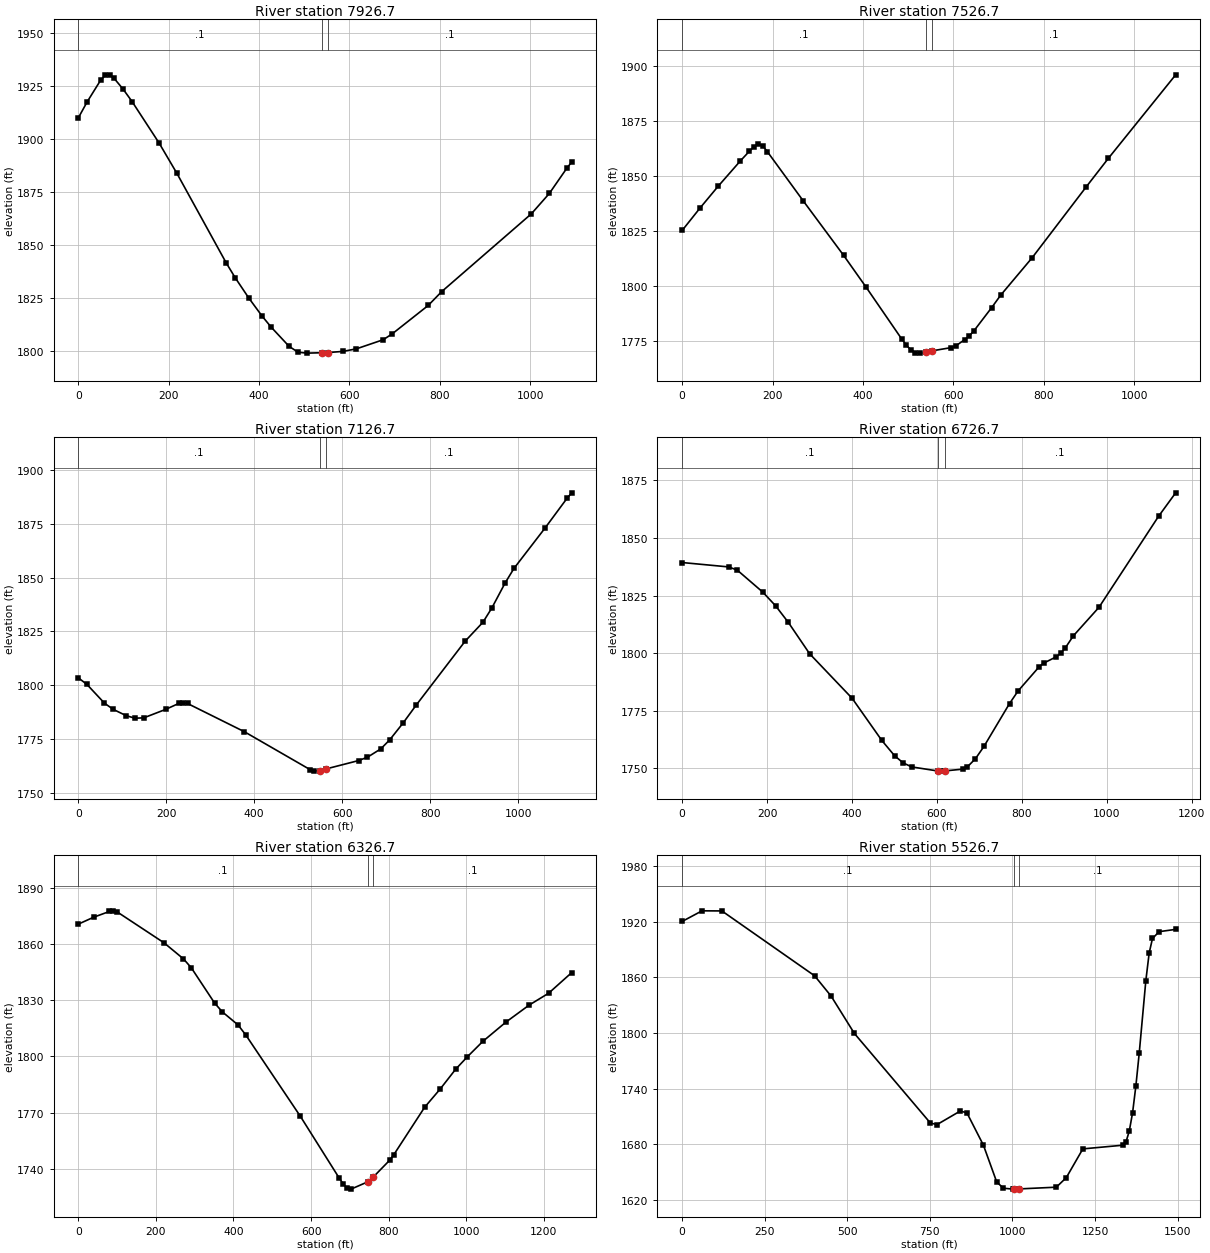
Type RM Length L Ch R = 1 ,7926.7,400,400,400
XS GIS Cut Line= 3
     2094692.595      265356.372     2095238.595      265356.372
     2095784.595      265356.372
#Sta/Elev= 30
       0 1909.91    19.8 1917.56    49.6 1927.76    59.6 1930.03    69.5 1930.29
    79.4 1928.63    99.3 1923.55   119.1 1917.71   178.7 1898.23   218.4 1883.84
   327.6 1841.59   347.4 1834.64   377.2 1825.16   407.0 1816.53   426.9 1811.38
   466.6 1802.32   486.4 1799.54   506.3 1799.12   538.5 1799.30   553.5 1799.41
   585.7 1799.93   615.5 1801.14   675.0 1805.45   694.9 1808.22   774.3 1821.57
   804.1 1828.08  1002.6 1864.77  1042.4 1874.37  1082.1 1886.58  1092.0 1889.18
#Mann= 3 , 0 , 0
       0     0.1       0   538.5   0.045       0   553.5     0.1       0
Bank Sta=   538.5,   553.5
Exp/Cntr=0.3,0.1

Type RM Length L Ch R = 1 ,7526.7,410.8,400,390.2
XS GIS Cut Line= 3
     2094692.595      265756.372     2095238.595      265756.372
     2095784.595      265756.372
#Sta/Elev= 30
       0 1825.19    39.7 1835.44    79.4 1845.25   129.0 1856.90   148.9 1861.28
   158.8 1863.30   168.8 1864.53   178.7 1863.62   188.6 1861.05   268.0 1838.64
   357.4 1813.83   407.0 1799.40   486.4 1775.63   496.4 1772.95   506.3 1770.76
   516.2 1769.55   526.2 1769.37   538.5 1769.80   553.5 1770.43   595.6 1771.89
   605.6 1772.69   625.4 1775.53   635.4 1777.27   645.3 1779.43   685.0 1790.12
   704.8 1795.74   774.3 1812.74   893.4 1844.86   943.1 1858.03  1092.0 1896.03
#Mann= 3 , 0 , 0
       0     0.1       0   538.5   0.045       0   553.5     0.1       0
Bank Sta=   538.5,   553.5
Exp/Cntr=0.3,0.1

Type RM Length L Ch R = 1 ,7126.7,386.3,400,396.5
XS GIS Cut Line= 3
     2094779.051      266382.271     2095279.940      266139.247
     2095798.192      265913.184
#Sta/Elev= 30
       0 1803.43    19.9 1800.32    59.6 1791.63    79.5 1788.74   109.4 1785.78
   129.2 1784.62   149.1 1784.80   198.8 1788.72   228.7 1791.50   238.6 1791.90
   248.5 1791.47   377.8 1778.34   526.9 1760.76   536.8 1760.02   549.2 1760.18
   564.2 1761.08   637.5 1764.93   657.7 1766.50   688.0 1770.37   708.2 1774.55
   738.5 1782.35   768.8 1790.81   879.8 1820.45   920.2 1829.23   940.4 1835.85
   970.7 1847.53   990.9 1854.31  1061.6 1873.09  1112.0 1887.03  1122.1 1889.41
#Mann= 3 , 0 , 0
       0     0.1       0   549.2   0.045       0   564.2     0.1       0
Bank Sta=   549.2,   564.2
Exp/Cntr=0.3,0.1

Type RM Length L Ch R = 1 ,6726.7,395.1,400,409.5
XS GIS Cut Line= 3
     2094813.341      266493.413     2095423.590      266479.745
     2095892.929      266189.509
#Sta/Elev= 30
       0 1839.34   110.1 1837.42   130.1 1835.99   190.1 1826.44   220.2 1820.50
   250.2 1813.28   300.2 1799.69   400.3 1780.32   470.3 1761.98   500.3 1755.35
   520.3 1752.26   540.4 1750.50   602.9 1748.70   610.4 1748.66   617.9 1748.74
   660.6 1749.52   670.6 1750.31   690.7 1754.05   710.7 1759.38   770.9 1778.02
   791.0 1783.49   841.2 1794.11   851.2 1795.59   881.3 1798.38   891.3 1799.94
   901.4 1801.98   921.4 1807.50   981.6 1819.87  1122.1 1859.48  1162.2 1869.64
#Mann= 3 , 0 , 0
       0     0.1       0   602.9   0.045       0   617.9     0.1       0
Bank Sta=   602.9,   617.9
Exp/Cntr=0.3,0.1

Type RM Length L Ch R = 1 ,6326.7,780.7,800,807.3
XS GIS Cut Line= 3
     2094821.916      266588.007     2095533.867      266834.067
     2096045.131      266748.065
#Sta/Elev= 30
       0 1870.52    40.2 1874.27    80.4 1877.30    90.4 1877.64   100.4 1877.06
   221.0 1860.61   271.2 1852.03   291.3 1847.31   351.5 1828.46   371.6 1823.74
   411.8 1816.83   431.9 1811.44   572.5 1768.10   672.9 1735.08   683.0 1732.03
   693.0 1729.83   703.0 1729.31   745.8 1733.17   760.8 1735.87   803.1 1744.82
   813.1 1747.62   892.8 1772.98   932.7 1782.66   972.6 1793.22  1002.5 1799.79
  1042.4 1808.02  1102.2 1818.34  1162.0 1827.41  1211.9 1833.68  1271.7 1844.73
#Mann= 3 , 0 , 0
       0     0.1       0   745.8   0.045       0   760.8     0.1       0
Bank Sta=   745.8,   760.8
Exp/Cntr=0.3,0.1

Type RM Length L Ch R = 1 ,5526.7,390.8,400,429.7
XS GIS Cut Line= 3
     2094797.296      266718.678     2095533.867      267413.337
     2095978.349      267599.215
#Sta/Elev= 30
       0 1920.41    60.2 1931.89   120.3 1931.78   401.0 1861.76   451.1 1839.78
   521.3 1799.57   751.8 1702.68   771.9 1701.14   842.0 1715.71   862.1 1713.81
   912.2 1678.80   952.3 1639.22   972.4 1632.39  1002.4 1631.40    1005 1631.40
    1020 1631.62  1132.9 1633.50  1163.0 1643.77  1213.2 1674.85  1333.6 1678.79
  1343.7 1682.32  1353.7 1693.97  1363.8 1713.96  1373.8 1743.06  1383.8 1777.90
  1403.9 1856.56  1414.0 1886.35  1424.0 1902.02  1444.1 1909.39  1494.2 1911.86
#Mann= 3 , 0 , 0
       0     0.1       0    1005   0.045       0    1020     0.1       0
Bank Sta=    1005,    1020
Exp/Cntr=0.3,0.1

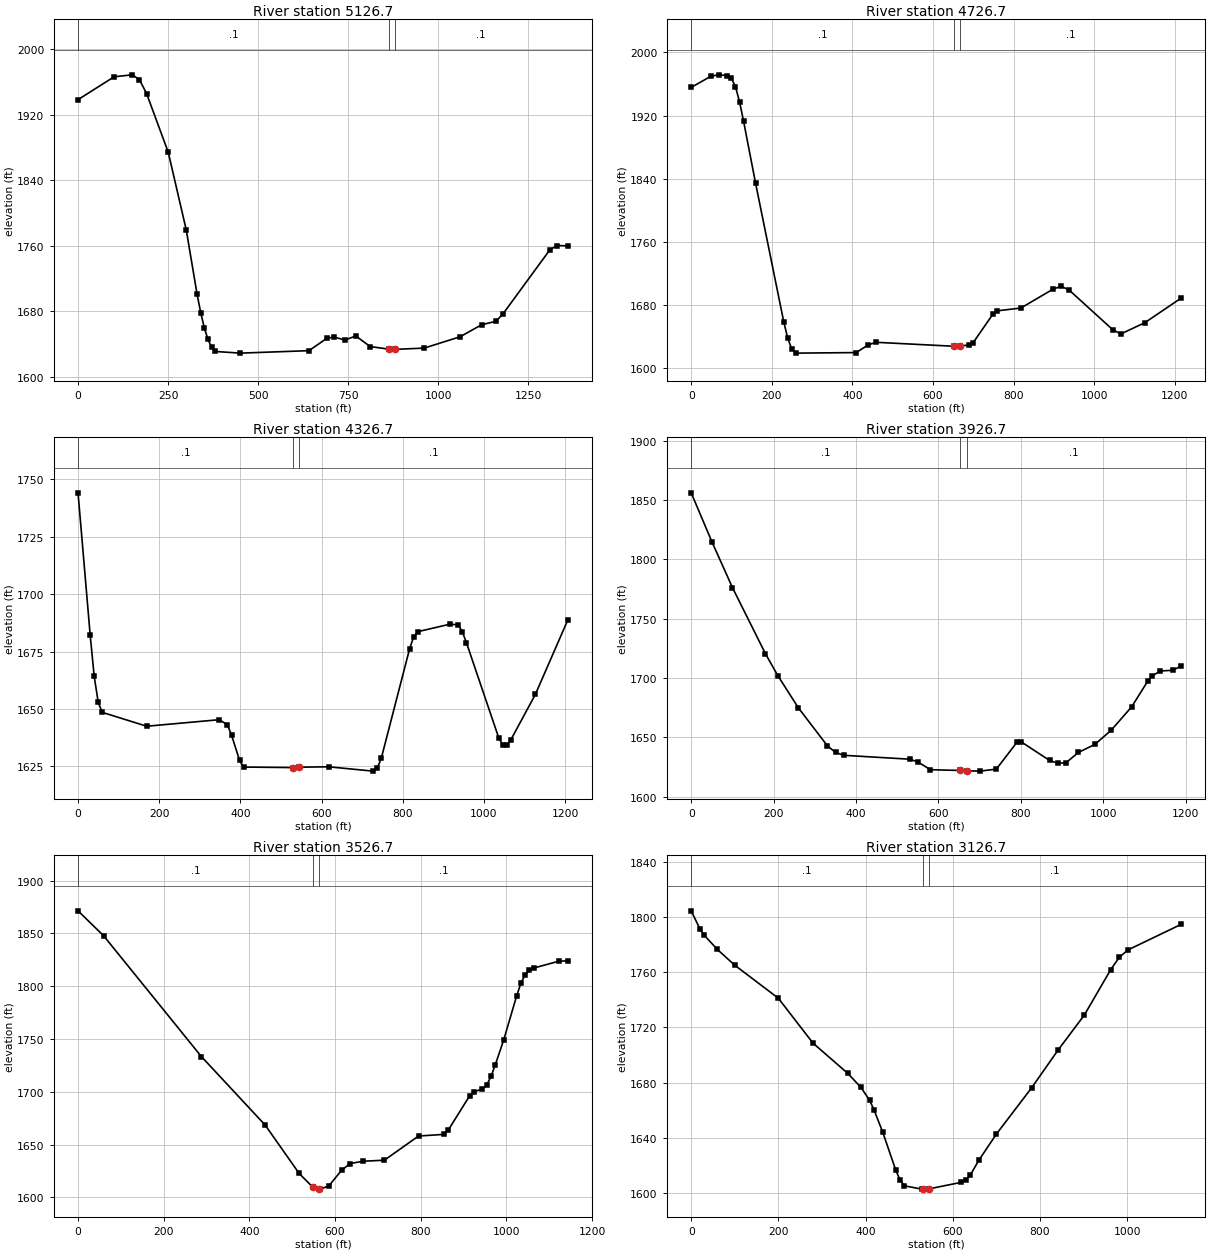
Type RM Length L Ch R = 1 ,5126.7,392.4,400,400
XS GIS Cut Line= 2
     2094722.711      266743.749     2095196.367      267475.837
#Sta/Elev= 30
       0 1938.44   100.2 1966.36   150.3 1968.76   170.4 1963.02   190.4 1945.92
   250.6 1874.14   300.7 1779.07   330.7 1700.73   340.8 1678.08   350.8 1659.60
   360.8 1645.57   370.8 1636.00   380.8 1630.70   451.0 1628.67   641.4 1631.67
   691.6 1646.90   711.6 1648.23   741.7 1644.75   771.7 1649.61   811.8 1636.64
   864.5 1633.51   879.5 1633.24   961.7 1634.82  1061.4 1648.70  1121.2 1663.38
  1161.0 1667.57  1181.0 1676.94  1310.6 1754.87  1330.5 1760.17  1360.4 1759.73
#Mann= 3 , 0 , 0
       0     0.1       0   864.5   0.045       0   879.5     0.1       0
Bank Sta=   864.5,   879.5
Exp/Cntr=0.3,0.1

Type RM Length L Ch R = 1 ,4726.7,405.5,400,391.2
XS GIS Cut Line= 3
     2094641.601      266747.745     2094837.136      267377.413
     2094836.382      267933.624
#Sta/Elev= 30
       0 1955.74    50.0 1970.15    69.9 1971.66    89.9 1970.67    99.9 1967.21
   109.9 1956.69   119.9 1937.66   129.9 1913.20   159.8 1834.29   229.8 1658.54
   239.8 1637.68   249.8 1623.94   259.7 1619.04   409.6 1619.73   439.6 1629.62
   459.5 1632.75   651.8 1627.75   666.8 1628.29   689.1 1629.18   699.1 1631.76
   748.7 1668.32   758.6 1672.58   818.2 1676.16   897.7 1699.98   917.6 1703.71
   937.4 1699.25  1046.7 1648.51  1066.6 1643.38  1126.2 1657.70  1215.5 1688.59
#Mann= 3 , 0 , 0
       0     0.1       0   651.8   0.045       0   666.8     0.1       0
Bank Sta=   651.8,   666.8
Exp/Cntr=0.3,0.1

Type RM Length L Ch R = 1 ,4326.7,406.2,400,384.1
XS GIS Cut Line= 3
     2094233.543      266862.373     2094498.911      267329.705
     2094742.078      267953.201
#Sta/Elev= 30
       0 1744.17    29.9 1682.20    39.8 1664.24    49.8 1652.78    59.7 1648.48
   169.2 1642.43   348.3 1645.28   368.2 1642.99   378.2 1638.58   398.1 1627.50
   408.0 1624.63   529.9 1624.41   544.9 1624.57   617.3 1624.75   727.2 1622.86
   737.2 1624.10   747.2 1628.44   817.1 1676.27   827.1 1681.38   837.1 1683.64
   917.0 1686.94   937.0 1686.57   947.0 1683.56   956.9 1678.89  1036.8 1637.28
  1046.8 1634.29  1056.8 1634.26  1066.8 1636.62  1126.8 1656.28  1206.7 1688.71
#Mann= 3 , 0 , 0
       0     0.1       0   529.9   0.045       0   544.9     0.1       0
Bank Sta=   529.9,   544.9
Exp/Cntr=0.3,0.1

Type RM Length L Ch R = 1 ,3926.7,389.7,400,408.5
XS GIS Cut Line= 3
     2093898.482      267097.139     2094326.433      267600.607
     2094670.137      268000.895
#Sta/Elev= 30
       0 1856.17    50.1 1815.02   100.1 1776.28   180.2 1720.51   210.2 1702.04
   260.3 1674.77   330.4 1642.91   350.4 1637.24   370.4 1634.86   530.6 1631.57
   550.6 1629.14   580.7 1622.71   653.3 1622.08   668.3 1621.76   700.6 1621.52
   740.4 1623.20   790.2 1645.71   800.1 1646.36   869.8 1630.50   889.7 1628.12
   909.6 1628.59   939.5 1637.28   979.3 1643.99  1019.1 1655.98  1068.9 1675.78
  1108.7 1697.84  1118.7 1701.90  1138.6 1705.94  1168.5 1706.56  1188.4 1710.05
#Mann= 3 , 0 , 0
       0     0.1       0   653.3   0.045       0   668.3     0.1       0
Bank Sta=   653.3,   668.3
Exp/Cntr=0.3,0.1

Type RM Length L Ch R = 1 ,3526.7,412.1,400,389
XS GIS Cut Line= 3
     2093801.679      267138.485     2093956.289      267672.685
     2094161.397      268223.077
#Sta/Elev= 30
       0 1871.29    59.6 1847.75   288.0 1733.33   437.0 1668.44   516.4 1622.64
   548.6 1609.48   563.6 1607.88   566.1 1607.81   586.0 1611.03   615.9 1625.92
   635.8 1632.06   665.6 1634.22   715.4 1635.20   795.0 1658.09   854.8 1659.65
   864.7 1663.86   914.5 1696.21   924.5 1700.09   944.4 1702.53   954.3 1706.42
   964.3 1714.51   974.2 1725.46   994.2 1749.43  1024.0 1790.61  1034.0 1802.67
  1043.9 1810.79  1053.9 1815.10  1063.8 1817.08  1123.6 1823.71  1143.5 1823.85
#Mann= 3 , 0 , 0
       0     0.1       0   548.6   0.045       0   563.6     0.1       0
Bank Sta=   548.6,   563.6
Exp/Cntr=0.3,0.1

Type RM Length L Ch R = 1 ,3126.7,476.7,458.9,441.8
XS GIS Cut Line= 3
     2093264.141      267506.612     2093645.437      267887.907
     2094071.438      268287.883
#Sta/Elev= 30
       0 1804.43    20.0 1791.36    30.0 1786.73    59.9 1776.47    99.9 1765.04
   199.7 1741.18   279.6 1708.54   359.5 1686.59   389.4 1676.53   409.4 1667.13
   419.4 1660.20   439.4 1644.11   469.3 1616.58   479.3 1609.33   489.3 1605.18
   529.2 1602.80   531.7 1602.81   546.7 1603.07   619.8 1607.73   629.9 1609.23
   640.0 1612.83   660.1 1623.79   700.4 1642.78   781.0 1676.19   841.5 1703.46
   901.9 1728.89   962.4 1761.75   982.5 1770.93  1002.7 1776.20  1123.6 1794.55
#Mann= 3 , 0 , 0
       0     0.1       0   531.7   0.045       0   546.7     0.1       0
Bank Sta=   531.7,   546.7
Exp/Cntr=0.3,0.1

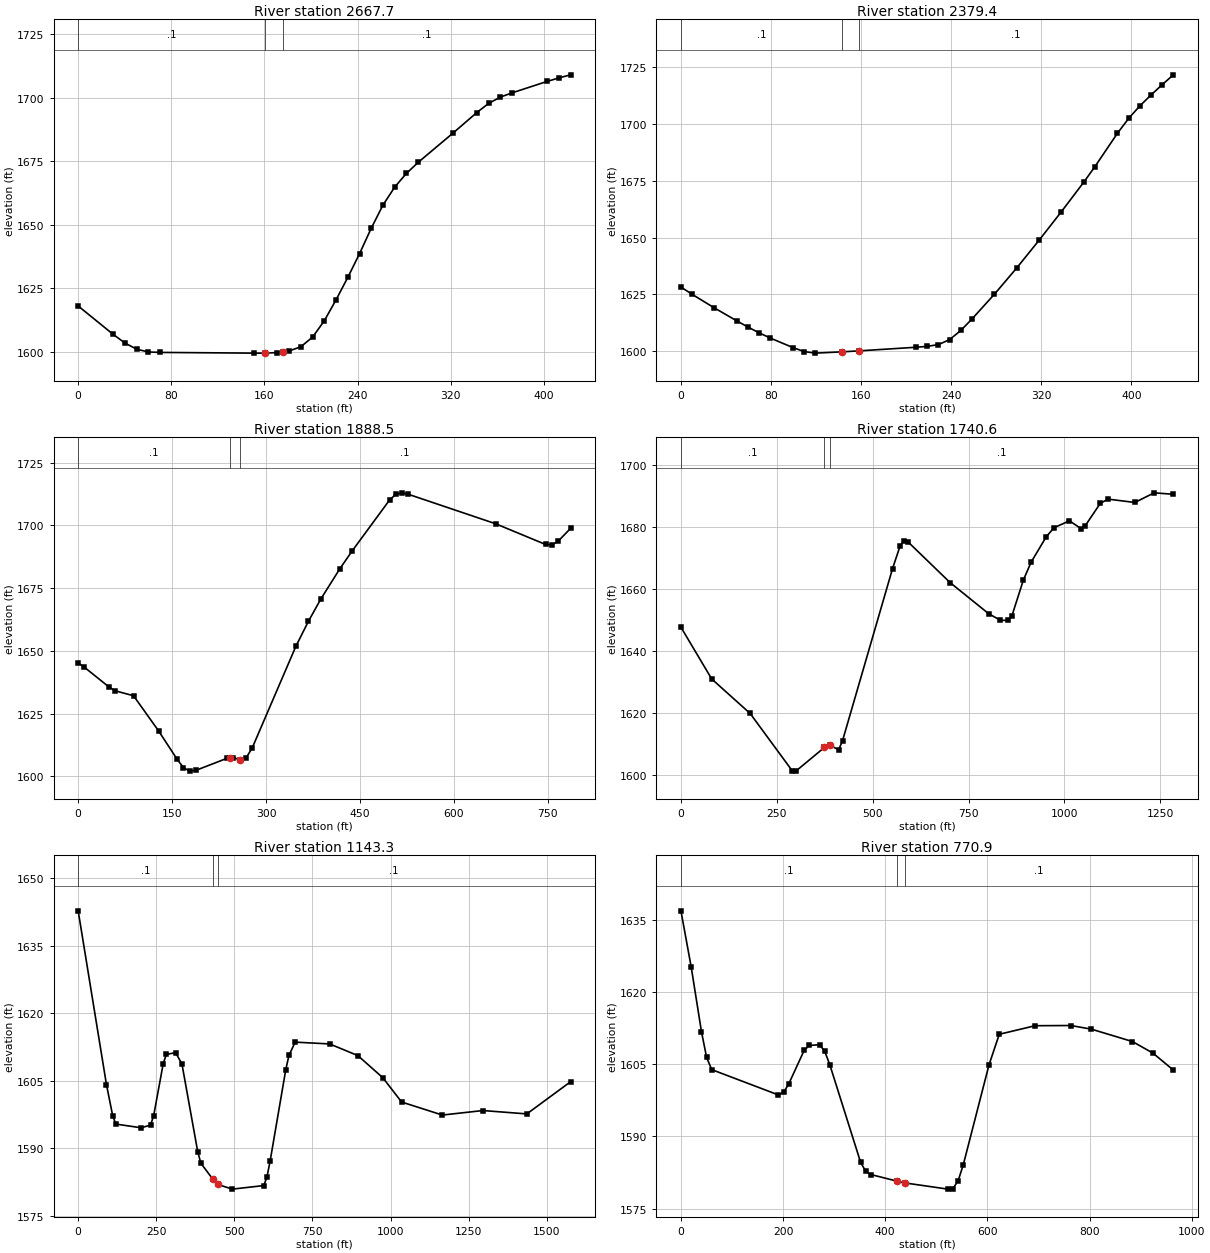
Type RM Length L Ch R = 1 ,2667.7,291.1,288.3,285.6
XS GIS Cut Line= 2
     2093298.831      268266.621     2093721.599      268282.376
#Sta/Elev= 30
       0 1618.00    30.2 1606.78    40.3 1603.39    50.4 1600.95    60.4 1599.90
    70.5 1599.72   151.1 1599.44   160.7 1599.44   171.2 1599.67   175.7 1599.95
   181.3 1600.30   191.4 1601.98   201.5 1605.79   211.5 1612.20   221.6 1620.44
   231.7 1629.30   241.8 1638.64   251.8 1648.61   261.9 1657.75   272.0 1664.82
   282.0 1670.18   292.1 1674.54   322.3 1686.17   342.5 1694.16   352.6 1697.73
   362.6 1700.22   372.7 1701.90   402.9 1706.41   413.0 1707.79   423.1 1709.01
#Mann= 3 , 0 , 0
       0     0.1       0   160.7   0.045       0   175.7     0.1       0
Bank Sta=   160.7,   175.7
Exp/Cntr=0.3,0.1

Type RM Length L Ch R = 1 ,2379.4,485.9,490.9,495.9
XS GIS Cut Line= 2
     2093317.213      268573.849     2093753.110      268537.087
#Sta/Elev= 30
       0 1628.15     9.9 1624.95    29.8 1618.92    49.7 1613.21    59.6 1610.48
    69.6 1607.92    79.5 1605.62    99.4 1601.47   109.4 1599.70   119.3 1599.00
   142.8 1599.56   157.8 1599.98   208.8 1601.59   218.7 1601.98   228.7 1602.76
   238.6 1604.95   248.6 1608.99   258.5 1614.05   278.4 1624.95   298.3 1636.59
   318.1 1648.78   338.0 1661.44   357.9 1674.46   367.8 1681.32   387.7 1695.97
   397.7 1702.54   407.6 1708.05   417.6 1712.89   427.5 1717.43   437.4 1721.76
#Mann= 3 , 0 , 0
       0     0.1       0   142.8   0.045       0   157.8     0.1       0
Bank Sta=   142.8,   157.8
Exp/Cntr=0.3,0.1

Type RM Length L Ch R = 1 ,1888.5,146.1,148,149.9
XS GIS Cut Line= 3
     2093395.280      268919.346     2093431.819      268999.829
     2094123.730      269090.256
#Sta/Elev= 30
       0 1645.17     9.8 1643.54    49.1 1635.67    58.9 1634.14    88.4 1632.16
   128.3 1618.19   158.2 1606.77   168.1 1603.54   178.1 1602.13   188.1 1602.45
   237.9 1607.27   242.9 1607.37   247.9 1607.47   257.9 1606.71   267.8 1607.30
   277.8 1611.33   347.6 1651.87   367.5 1661.78   387.4 1670.69   417.4 1682.61
   437.3 1689.80   497.1 1710.12   507.1 1712.42   517.0 1713.00   527.0 1712.43
   666.6 1700.67   746.3 1692.42   756.3 1692.24   766.2 1693.70   786.2 1698.86
#Mann= 3 , 0 , 0
       0     0.1       0   242.9   0.045       0   257.9     0.1       0
Bank Sta=   242.9,   257.9
Exp/Cntr=0.3,0.1

Type RM Length L Ch R = 1 ,1740.6,560.1,597.3,629.3
XS GIS Cut Line= 2
     2093225.252      269085.463     2094478.669      269364.722
#Sta/Elev= 30
       0 1647.61    80.3 1630.93   180.6 1619.81   290.9 1601.24   301.0 1601.37
   374.2 1608.87   389.2 1609.52   411.3 1608.12   421.4 1611.02   551.8 1666.47
   571.8 1673.86   581.9 1675.50   591.9 1675.13   702.3 1661.94   802.6 1651.95
   832.7 1649.87   852.8 1649.77   862.8 1651.14   892.9 1662.75   913.0 1668.52
   953.1 1676.81   973.1 1679.68  1013.3 1681.88  1043.4 1679.35  1053.4 1680.13
  1093.5 1687.48  1113.6 1688.88  1183.8 1687.79  1234.0 1690.90  1284.2 1690.43
#Mann= 3 , 0 , 0
       0     0.1       0   374.2   0.045       0   389.2     0.1       0
Bank Sta=   374.2,   389.2
Exp/Cntr=0.3,0.1

Type RM Length L Ch R = 1 ,1143.3,374.9,372.4,369.8
XS GIS Cut Line= 3
     2093168.434      269108.251     2093226.299      269810.658
     2094079.172      269989.582
#Sta/Elev= 30
       0 1642.74    90.6 1604.16   110.8 1597.17   120.8 1595.41   201.4 1594.60
   231.6 1595.18   241.6 1597.25   271.8 1608.67   281.9 1610.87   312.1 1611.27
   332.3 1608.70   382.6 1589.32   392.7 1586.72   431.7 1583.13   446.7 1582.03
   493.4 1580.98   594.0 1581.77   604.1 1583.64   614.2 1587.13   664.5 1607.49
   674.6 1610.65   694.7 1613.60   805.0 1613.20   895.1 1610.62   975.2 1605.70
  1035.3 1600.31  1165.6 1597.42  1295.8 1598.42  1436.0 1597.67  1576.2 1604.82
#Mann= 3 , 0 , 0
       0     0.1       0   431.7   0.045       0   446.7     0.1       0
Bank Sta=   431.7,   446.7
Exp/Cntr=0.3,0.1

Type RM Length L Ch R = 1 ,770.9,305.9,302.5,299
XS GIS Cut Line= 3
     2092749.539      269142.132     2092869.830      269753.727
     2093199.461      269840.478
#Sta/Elev= 30
       0 1636.90    20.1 1625.24    40.2 1611.78    50.3 1606.42    60.3 1603.88
   191.0 1598.61   201.1 1599.16   211.1 1600.91   241.3 1607.88   251.3 1608.91
   271.4 1609.06   281.5 1607.71   291.6 1604.87   351.9 1584.58   361.9 1582.72
   372.0 1582.06   422.8 1580.70   437.8 1580.33   522.8 1579.03   532.8 1579.16
   542.9 1580.81   552.9 1584.11   603.2 1604.86   623.3 1611.23   693.5 1613.01
   763.7 1613.05   803.8 1612.29   884.0 1609.72   924.1 1607.32   964.2 1603.78
#Mann= 3 , 0 , 0
       0     0.1       0   422.8   0.045       0   437.8     0.1       0
Bank Sta=   422.8,   437.8
Exp/Cntr=0.3,0.1

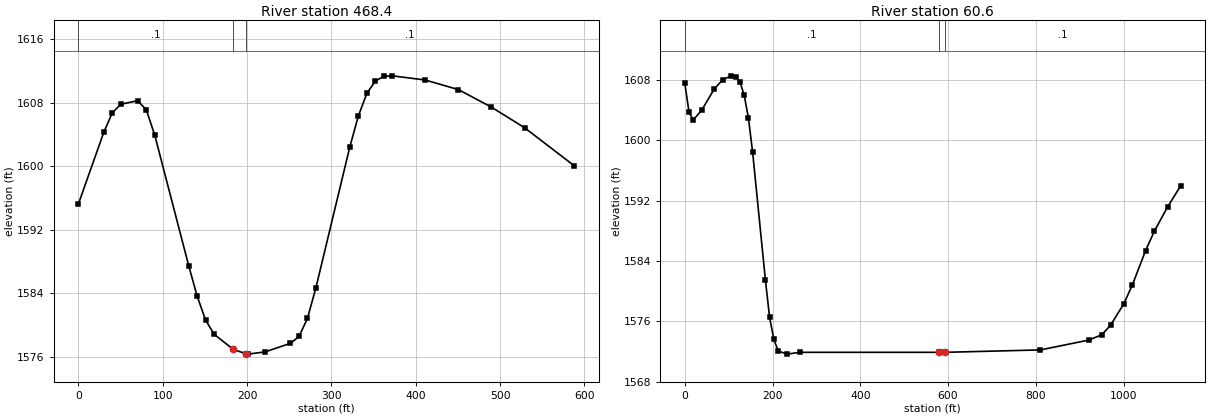
Type RM Length L Ch R = 1 ,468.4,430.7,407.9,385
XS GIS Cut Line= 3
     2092466.731      269398.820     2092590.717      269749.761
     2092798.760      269806.500
#Sta/Elev= 30
       0 1595.22    30.2 1604.29    40.2 1606.72    50.3 1607.82    70.4 1608.26
    80.5 1607.13    90.5 1603.96   130.8 1587.48   140.8 1583.65   150.9 1580.60
   161.0 1578.82   183.8 1576.91   198.8 1576.36   201.2 1576.32   221.3 1576.60
   251.5 1577.68   261.6 1578.55   271.6 1580.82   281.7 1584.71   321.9 1602.47
   332.0 1606.35   342.0 1609.18   352.1 1610.75   362.1 1611.33   372.2 1611.40
   411.4 1610.87   450.6 1609.66   489.8 1607.45   529.0 1604.86   587.8 1600.07
#Mann= 3 , 0 , 0
       0     0.1       0   183.8   0.045       0   198.8     0.1       0
Bank Sta=   183.8,   198.8
Exp/Cntr=0.3,0.1

Type RM Length L Ch R = 1 ,60.6,64.2,60.6,56.9
XS GIS Cut Line= 4
     2091783.693      269587.476     2091914.731      269754.860
     2092436.669      269885.685     2092810.430      269820.130
#Sta/Elev= 30
       0 1607.58     9.7 1603.72    19.3 1602.72    38.6 1604.02    67.6 1606.87
    87.0 1608.08   106.3 1608.57   116.0 1608.48   125.6 1607.78   135.3 1606.01
   144.9 1603.03   154.6 1598.44   183.6 1581.53   193.2 1576.54   202.9 1573.62
   212.6 1572.08   232.5 1571.64   262.4 1571.88   578.6 1571.88   593.6 1571.88
   810.6 1572.20   920.4 1573.50   950.4 1574.21   970.4 1575.48  1000.3 1578.28
  1020.3 1580.85  1050.2 1585.37  1070.2 1587.95  1100.2 1591.16  1130.1 1593.96
#Mann= 3 , 0 , 0
       0     0.1       0   578.6   0.045       0   593.6     0.1       0
Bank Sta=   578.6,   593.6
Exp/Cntr=0.3,0.1